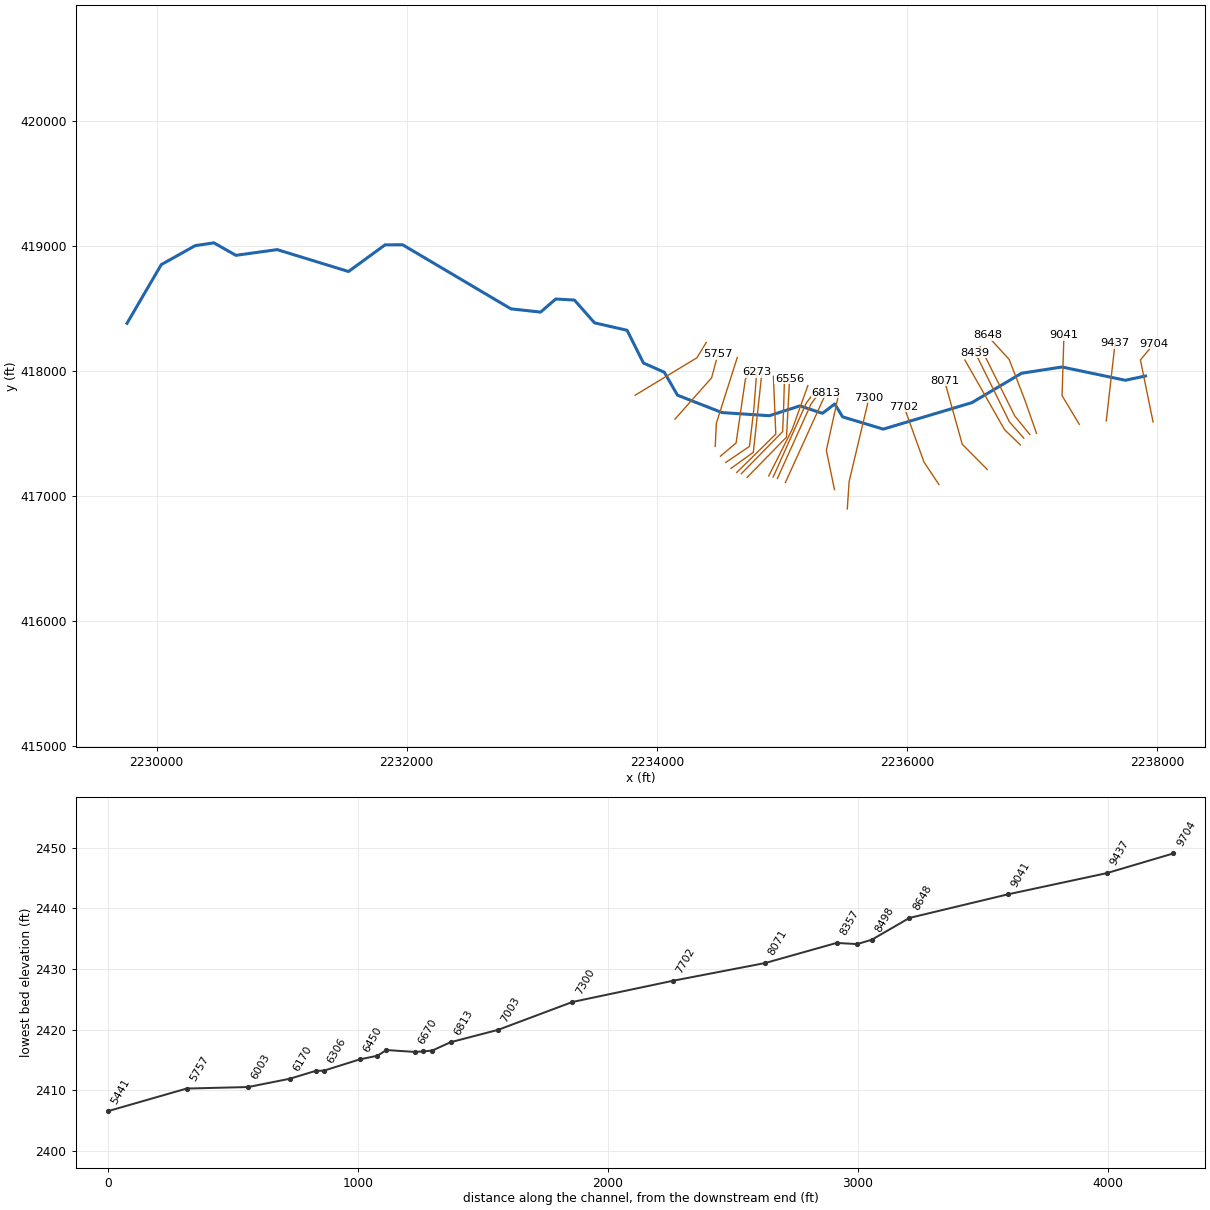
--- NFBEAVERCK.prj (project) ---

Proj Title=NFBEAVERCK
Current Plan=p01
Default Exp/Contr=0,0
English Units
Geom File=g01
Flow File=f01
Plan File=p01
Background Map Layer=Inundation Boundary (01pct Value_0)
Background Map Layer=Inundation Boundary (01pct Value_0)
BEGIN DESCRIPTION:
----------MODEL BY WOOD PLC 2021----------
Stream Name: North Fork Beaver Creek
Flood Zone: Approximate
Pocahontas County, WV
HEC-RAS Version: RAS 6.1
Vertical Datum: NAVD88
Projection: NAD 1983 StatePlane West Virginia S FIPS 4702 (US Feet)
Terrain: 1-meter LIDAR (FEMA Region III 3DEP collected 2016-2018)
Land Use: 2019 NLCD
Hydrologic Method:
WV SIR2010-5033 regression equations
END DESCRIPTION:
DSS File=dss
DSS Export Rating Curves= 0
DSS Export Rating Curve Sorted= 0
DSS Export Volume Flow Curves= 0
DXF OffsetX= 0
DXF OffsetY= 0
DXF ScaleX= 0
DXF ScaleY= 0

--- NFBEAVERCK.p01 (plan) ---

Plan Title=Floodplain
Program Version=6.10
Short Identifier=Floodplain
Geom File=g01
Flow File=f01
Subcritical Flow
K Sum by GR= 0
Std Step Tol= 0.01
Critical Tol= 0.01
Num of Std Step Trials= 20
Max Error Tol= 0.3
Flow Tol Ratio= 0.001
Split Flow NTrial= 30
Split Flow Tol= 0.02
Split Flow Ratio= 0.02
Log Output Level= 0
Friction Slope Method= 1
Unsteady Friction Slope Method= 2
Unsteady Bridges Friction Slope Method= 1
Parabolic Critical Depth
Global Vel Dist= 0 , 0 , 0
Global Log Level= 0
CheckData=True
Encroach Param=-1 ,0,0, 0
Computation Interval=0.1SEC
Output Interval=1SEC
Instantaneous Interval=Max Profile
Mapping Interval=1HOUR
Computation Time Step Use Courant=        0
Computation Time Step Use Time Series=    0
Computation Time Step Count To Double=0
Computation Time Step Max Doubling=0
Computation Time Step Max Halving=0
Computation Time Step Residence Courant=0
Run HTab= 0
Run UNet= 0
Run Sediment= 0
Run PostProcess= 0
Run WQNet= 0
Run RASMapper= 0
UNET Theta= 0
UNET Theta Warmup= 0
UNET ZTol= 0
UNET ZSATol= 0
UNET MxIter= 0
UNET Max Iter WO Improvement= 0
UNET MaxInSteps= 0
UNET DtIC= 0
UNET DtMin= 0
UNET MaxCRTS= 0
UNET WFStab= 0
UNET SFStab= 0
UNET WFX= 1
UNET SFX= 1
UNET Gravity=32.174
UNET 1D Methodology=Finite Difference
UNET DSS MLevel= 1
UNET Pardiso=0
UNET DZMax Abort= 0
UNET Use Existing IB Tables= 0
UNET Froude Reduction=False
UNET Froude Limit= 0
UNET Froude Power= 0
UNET D1 Cores= 0
UNET WindReference=Eulerian
UNET WindDragFormulation=Hsu (1988)
UNET D2 Coriolis=0
UNET D2 Cores= 0
UNET D2 Theta= 1
UNET D2 Theta Warmup= 1
UNET D2 Z Tol= 0.01
UNET D2 Volume Tol= 0.01
UNET D2 Max Iterations= 20
UNET D2 Equation= 0
UNET D2 RampUpFraction=0.1
UNET D2 TimeSlices= 1
UNET D2 Turbulence Formulation=Non-Conservative (original)
UNET D2 Eddy Viscosity=0.3
UNET D2 Transverse Eddy Viscosity=0.1
UNET D2 Smagorinsky Mixing=0
UNET D2 BCVolumeCheck=0
UNET D2 Cores=0
UNET D2 SolverType=PARDISO (Direct)
UNET D2 Minimum Iterations= 2147483647
UNET D2 Maximum Iterations= 2147483647
UNET D2 Restart Number= 10
UNET D2 Relaxation Coeff=1.3
UNET D2 SOR Precondition Iterations= 10
UNET D2 ILUT Maximum Fill= 8
UNET D2 ILUT Tolerance=1E-08
UNET D1D2 MaxIter= 0
UNET D1D2 ZTol=0.01
UNET D1D2 QTol=0.1
UNET D1D2 MinQTol=1
DSS File=dss
Write IC File= 0
Write IC File at Fixed DateTime=0
Write IC File at Sim End=0
Echo Input=False
Echo Parameters=False
Echo Output=False
Write Detailed= 0
HDF Write Warmup=0
HDF Write Time Slices=0
HDF Flush=0
HDF Compression= 1
HDF Chunk Size= 1
HDF Spatial Parts= 1
HDF Use Max Rows=0
HDF Fixed Rows= 1
Calibration Method= 0
Calibration Iterations= 20
Calibration Max Change=0.05
Calibration Tolerance=0.2
Calibration Maximum=1.5
Calibration Minimum=0.5
Calibration Optimization Method= 1
WQ AD Non Conservative
WQ ULTIMATE=-1
WQ Max Comp Step=1HOUR
WQ Output Interval=15MIN
WQ Output Selected Increments= 0
WQ Output face flow=0
WQ Output face velocity=0
WQ Output face area=0
WQ Output face dispersion=0
WQ Output cell volume=0
WQ Output cell surface area=0
WQ Output cell continuity=0
WQ Output cumulative cell continuity=0
WQ Output face conc=0
WQ Output face dconc_dx=0
WQ Output face courant=0
WQ Output face peclet=0
WQ Output face adv mass=0
WQ Output face disp mass=0
WQ Output cell mass=0
WQ Output cell source sink temp=0
WQ Output nsm pathways=0
WQ Output nsm derived pathways=0
WQ Create Restart=0
WQ Fixed Restart=0
WQ System Summary=0
WQ Write To DSS=0
Sorting and Armoring Iterations= 10
XS Update Threshold= 0.02
Bed Roughness Predictor= 0
Hydraulics Update Threshold= 0.02
Energy Slope Method= 1
Volume Change Method= 1
Sediment Retention Method= 0
Sediment TS Multiplier= 1
Warm Up Method= 0
XS Weighting Method= 0
Number of US Weighted Cross Sections= 1
Number of DS Weighted Cross Sections= 1
Upstream XS Weight=0
Main XS Weight=1
Downstream XS Weight=0
Number of DS XS's Weighted with US Boundary= 1
Upstream Boundary Weight= 1
Weight of XSs Associated with US Boundary= 0
Number of US XS's Weighted with DS Boundary= 1
Downstream Boundary Weight= 0.5
Weight of XSs Associated with DS Boundary= 0.5
Percentile Method= 0
Sediment Output Level= 3
Mass or Volume Output= 0
Output Increment Type= 1
Profile and TS Output Increment= 1
Transport Output Increment 1
XS Output Flag= 0
XS Output Increment= 10
Read HDF5 Sediment Hotstart= 0
Sediment Hotstart Type= 0
Write Gradation File= 0
Read Gradation Hotstart= 0
Write HDF5 File= 1
Write Binary Output= 1
Write DSS Sediment File= 0
DSS Sediment Output Type= 1
SV Curve= 0
Specific Gage Flag= 0
Subcell Erosion Methods= 0
Subcell Deposition Methods= 0
Advection Scheme= 1
Matrix Solver= 0
Implicit Weighting Factor= 1
Maximum Outer Loop Convergence Iterations= 5
Convergence Maximum Absolute= 0.001
Convergence RMSE= 0.0001
Grain Fractions Max Abs Error= 0.001
Max Subgrid Regions= 1
Max Subgrid Length Scale= 3.402823E+38
Initial Layer Thickness= 3.402823E+38
Min Layer Thickness= 3.402823E+38
Max Layer Thickness= 3.402823E+38
Number of Layers= 5

--- NFBEAVERCK.f01 (steady flow) ---

Flow Title=Flow
Program Version=6.10
Number of Profiles= 6
Profile Names=01pct,10pct,04pct,02pct,0_2pct,01plus
River Rch & RM=NFBEAVERCK,Main            ,9704
     654     347     461     554     911     967
River Rch & RM=NFBEAVERCK,Main            ,3349
     939     506     667     799    1300    1390
Boundary for River Rch & Prof#=NFBEAVERCK,Main            , 1
Up Type= 0
Dn Type= 3
Dn Slope=0.04472
Boundary for River Rch & Prof#=NFBEAVERCK,Main            , 2
Up Type= 0
Dn Type= 3
Dn Slope=0.04472
Boundary for River Rch & Prof#=NFBEAVERCK,Main            , 3
Up Type= 0
Dn Type= 3
Dn Slope=0.04472
Boundary for River Rch & Prof#=NFBEAVERCK,Main            , 4
Up Type= 0
Dn Type= 3
Dn Slope=0.04472
Boundary for River Rch & Prof#=NFBEAVERCK,Main            , 5
Up Type= 0
Dn Type= 3
Dn Slope=0.04472
Boundary for River Rch & Prof#=NFBEAVERCK,Main            , 6
Up Type= 0
Dn Type= 3
Dn Slope=0.04472
DSS Import GetInterval= 0
DSS Import GetPeak= 0
DSS Import FillOption= 0

--- NFBEAVERCK.g01 (geometry) ---

Geom Title=Geometry
Program Version=6.10

River Reach=NFBEAVERCK      ,Main
Reach XY= 30
2237908.25500001417961.4700000142237746.12821319417927.319905272
2237240.67099999418033.379277742     2236917.395417983.587000012
     2236519.656417748.1580000222235810.77304736417536.586440809
2235485.73900004417634.626000017     2235422.642417737.740999997
2235325.03346448417662.9483460612235143.71736978 417722.33890528
     2234900.057417643.6620000152234521.38900004417668.980000019
2234165.46600001417807.716999993 2234060.0787433417991.236322776
2233893.43795267418065.0074408132233762.48200001418326.839000002
 2233501.7120474418386.507952633     2233341.145418568.707000017
2233191.44508206418577.055894135     2233070.661418472.518000022
2232833.87199999418498.0730000142231967.40499999419010.768000022
 2231826.8479331419010.2880000032231534.30999999418797.002000004
2230964.08300002418972.109999999     2230633.767418926.428000003
2230457.86100002419026.3020000162230308.06800003419003.795000017
2230037.01100002418851.9750000092229763.14149575 418382.91266714

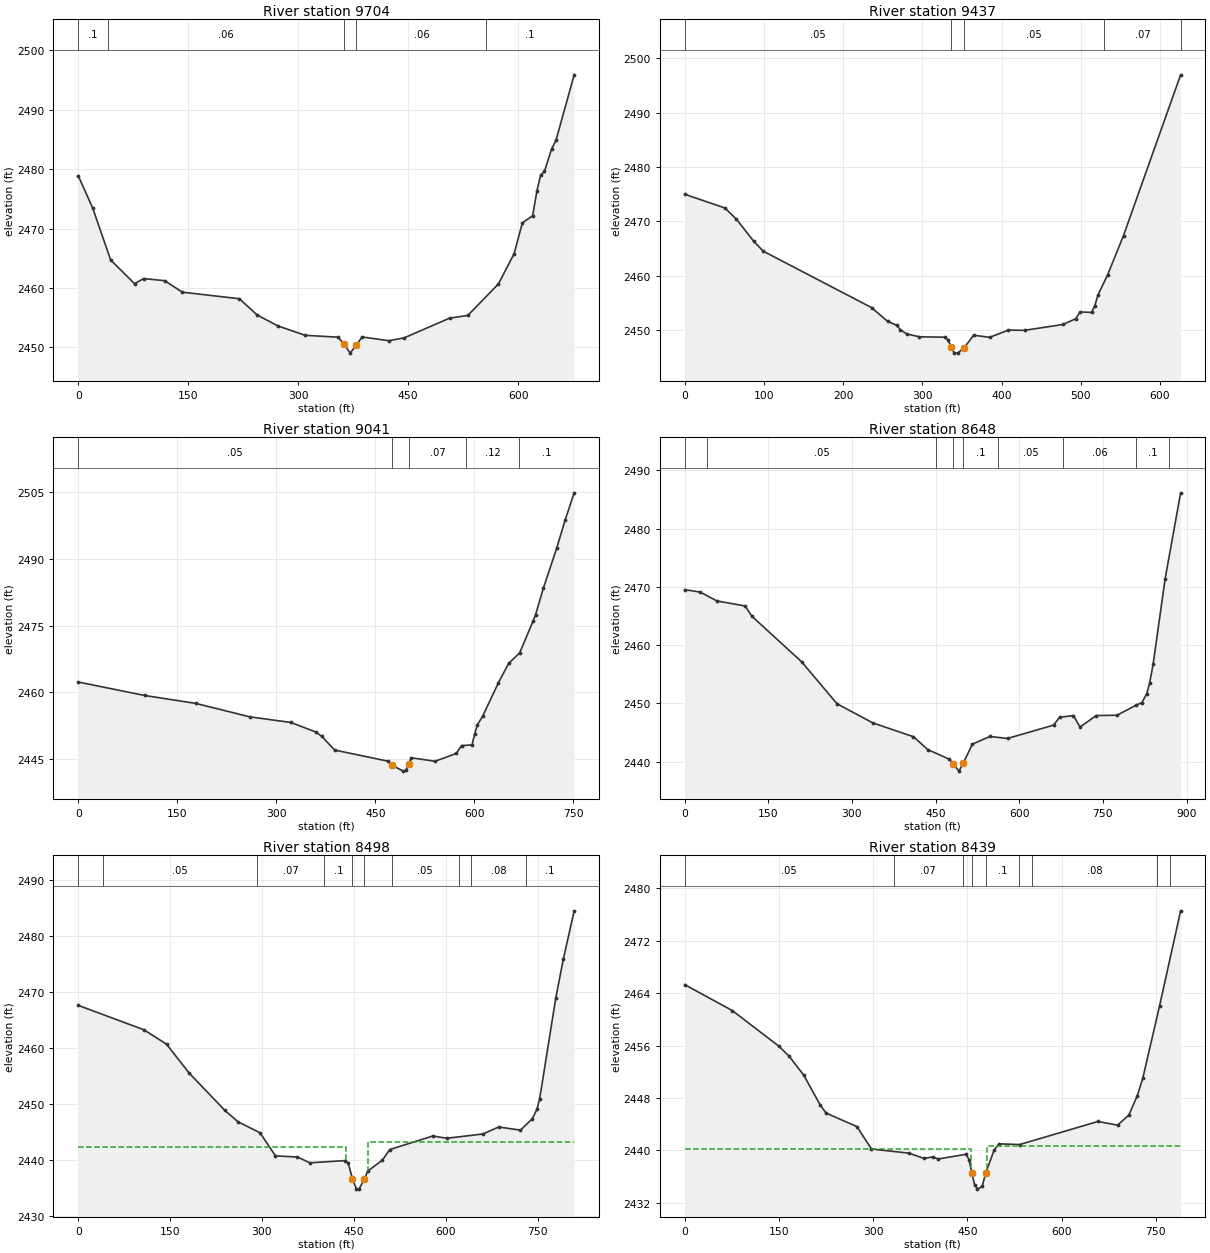
Type RM Length L Ch R = 1 ,9704    ,271.9,266.4,260.4
XS GIS Cut Line= 3
2237968.47160843 417593.870979932237867.34500803418090.118566283
2237976.60135344418220.141246964
#Sta/Elev= 30
       0 2478.88    19.7 2473.46    44.2 2464.72    76.9 2460.71    89.1 2461.58
   117.7 2461.23   142.1 2459.29   219.7 2458.19   244.2 2455.44   272.8 2453.59
   309.5 2452.04   354.4 2451.72   362.8 2450.51   370.8 2449.04379.45072450.408
   387.1 2451.76   423.6 2451.13   444.3  2451.6   506.4 2454.92   531.3 2455.38
   573.1 2460.69   594.4 2465.76   605.7 2470.95   619.7 2472.15   625.6 2476.37
   630.6 2478.97   635.8  2479.6   645.5 2483.37   651.5 2484.81   676.3 2495.85
#Mann= 5 ,-1,0
       0      .1       0      40     .06       0   362.8    .045       0
379.4507     .06       0  556.45      .1       0
Bank Sta=362.8,379.4507
XS Rating Curve= 0 ,0
Exp/Cntr=0.3,0.1

Type RM Length L Ch R = 1 ,9437    ,393.2,396.9,397
XS GIS Cut Line= 2
2237594.38043082417602.7076571332237664.92526862418224.784863159
#Sta/Elev= 30
       0    2475    50.8 2472.47    65.3 2470.42      87 2466.38    99.1 2464.54
     236 2454.15   256.1 2451.64   268.2 2450.87   272.2 2450.09   280.3 2449.32
   296.4 2448.79   328.6 2448.72   332.6 2448.21   336.5 2446.83   340.6 2445.79
   344.7 2445.81   352.7 2446.75   364.8 2449.08   384.9 2448.69   408.8 2450.03
   429.2 2449.98   477.5 2451.06   493.6  2452.1   499.2 2453.36   513.7 2453.28
   517.8 2454.53   521.8  2456.5   533.9 2460.17     554  2467.4   626.1 2496.95
#Mann= 5 ,-1,0
       0     .05       0   336.5    .045       0   352.7     .05       0
     530     .07       0  626.06      .1       0
Bank Sta=336.5,352.7
XS Rating Curve= 0 ,0
Exp/Cntr(USF)=0,0
Exp/Cntr=0.3,0.1

Type RM Length L Ch R = 1 ,9041    ,383.2,392.7,396.7
XS GIS Cut Line= 3
2237378.58625354417574.860636376 2237240.8919248 417804.34434314
2237255.85628223418287.687790748
#Sta/Elev= 30
       0 2462.33   100.7  2459.3   178.4 2457.51     260 2454.49   322.1 2453.23
   360.1 2451.07   368.7 2450.13   388.5 2447.02   468.6 2444.54   475.7 2443.55
   492.6 2442.28   496.6  2442.5   500.5 2443.88   504.6 2445.28   540.6  2444.5
   572.6 2446.25   580.6 2448.02   596.6 2448.19   600.6 2450.71   604.6  2452.7
   612.6 2454.64   636.6 2462.19     652 2466.52   668.7 2468.89   688.7 2475.96
   692.7 2477.45   704.7  2483.5   724.7 2492.42   737.4  2498.7   751.2  2504.9
#Mann= 5 ,-1,0
       0     .05       0   475.7    .045       0   500.5     .07       0
  587.62     .12       0  667.62      .1       0
Bank Sta=475.7,500.5
XS Rating Curve= 0 ,0
Exp/Cntr=0.3,0.1

Type RM Length L Ch R = 1 ,8648    ,148.9,150.3,151.3
XS GIS Cut Line= 4
2237036.30760642417503.3400100352236943.35280095417768.550795035
2236818.28182729418093.0569719022236642.68006021418285.636638534
#Sta/Elev= 30
       0 2469.52    27.4 2469.11      58 2467.58   108.3 2466.72   120.6 2464.95
   209.6 2457.16   273.2 2449.95   337.4 2446.67   410.3  2444.3     436 2442.09
   474.6 2440.44     482 2439.61   491.8  2438.4499.98532439.845     516 2443.03
   547.5 2444.34     579    2444   661.6 2446.29   672.3 2447.64   697.2 2447.92
   709.1 2445.96     738 2447.93   775.1 2447.98   808.8 2449.66   820.1 2450.16
   828.6 2451.68   833.8 2453.46   840.1 2456.74   861.7 2471.42   889.4 2486.12
#Mann= 9 ,-1,0
       0     .06       0      40     .05       0  451.03      .1       0
     482    .045       0499.9853      .1       0  561.03     .05       0
   678.8     .06       0   808.8      .1       0   868.8     .12       0
Bank Sta=482,499.9853
XS Rating Curve= 0 ,0
Exp/Cntr=0.5,0.3

Type RM Length L Ch R = 1 ,8498    ,58.5,58.4,58.6
XS GIS Cut Line= 3
2236983.03985359 417493.493040782236862.31602183417642.320427549
2236586.86004453418195.638637705
#Sta/Elev= 30
       0 2467.64     107 2463.29   144.2 2460.71     181 2455.56   239.5 2448.87
     261 2446.83   296.8 2444.88   322.1 2440.75     358 2440.55     378 2439.51
   436.1 2439.91   440.6 2439.53   447.8 2436.65     454 2434.88   458.5 2434.81
   467.4 2436.63   472.8 2438.04   496.7    2440   508.6 2441.88   579.1 2444.31
   601.4 2443.89   660.7 2444.66   686.3 2445.91   722.1 2445.35   741.3 2447.38
   748.9 2449.05   753.4 2450.96   779.8 2469.02     792 2475.88   809.7 2484.53
#Mann= 10 ,-1,0
       0     .06       0      40     .05       0  291.63     .07       0
  401.63      .1       0   447.8    .045       0   467.4      .1       0
  511.63     .05       0  621.63     .06       0  641.63     .08       0
  731.63      .1       0
#XS Ineff= 2 , 0
          437.19 2442.38  472.38         2443.25
Permanent Ineff=
       F       F
Bank Sta=447.8,467.4
XS Rating Curve= 0 ,0
Exp/Cntr(USF)=0,0
Exp/Cntr=0.5,0.3

Type RM Length L Ch R = 1 ,8439    ,81.6,82.6,83.5
XS GIS Cut Line= 3
2236934.55631053417464.7492259622236820.23923266417594.010039992
2236547.03427701418147.155094638
#Sta/Elev= 30
       0 2465.29    75.7 2461.34   150.1 2455.89   166.1 2454.38   189.5 2451.49
   216.2 2446.85   225.2 2445.69   274.2 2443.63   297.4 2440.21   357.1 2439.58
     381 2438.77   394.7 2439.01   403.6 2438.69   448.2 2439.41   452.7 2438.57
   457.2 2436.58   461.6 2434.69   466.1 2434.09   473.6  2434.5   479.1  2436.5
   492.8  2440.1   500.5    2441   533.3 2440.89   657.9 2444.41   689.1 2443.85
     707 2445.38   720.4 2448.31   729.3 2451.02   756.1 2462.09   789.5 2476.55
#Mann= 9 ,-1,0
       0     .05       0  332.56     .07       0  442.56      .1       0
   457.2    .045       0   479.1      .1       0  532.56     .05       0
  552.56     .08       0  752.56      .1       0  772.56     .12       0
#XS Ineff= 2 ,-1
       0  455.86  2440.2  481.53789.4957 2440.68
Permanent Ineff=
       F       F
Bank Sta=457.2,479.1
XS Rating Curve= 0 ,0
Exp/Cntr(USF)=0,0
Exp/Cntr=0.5,0.3

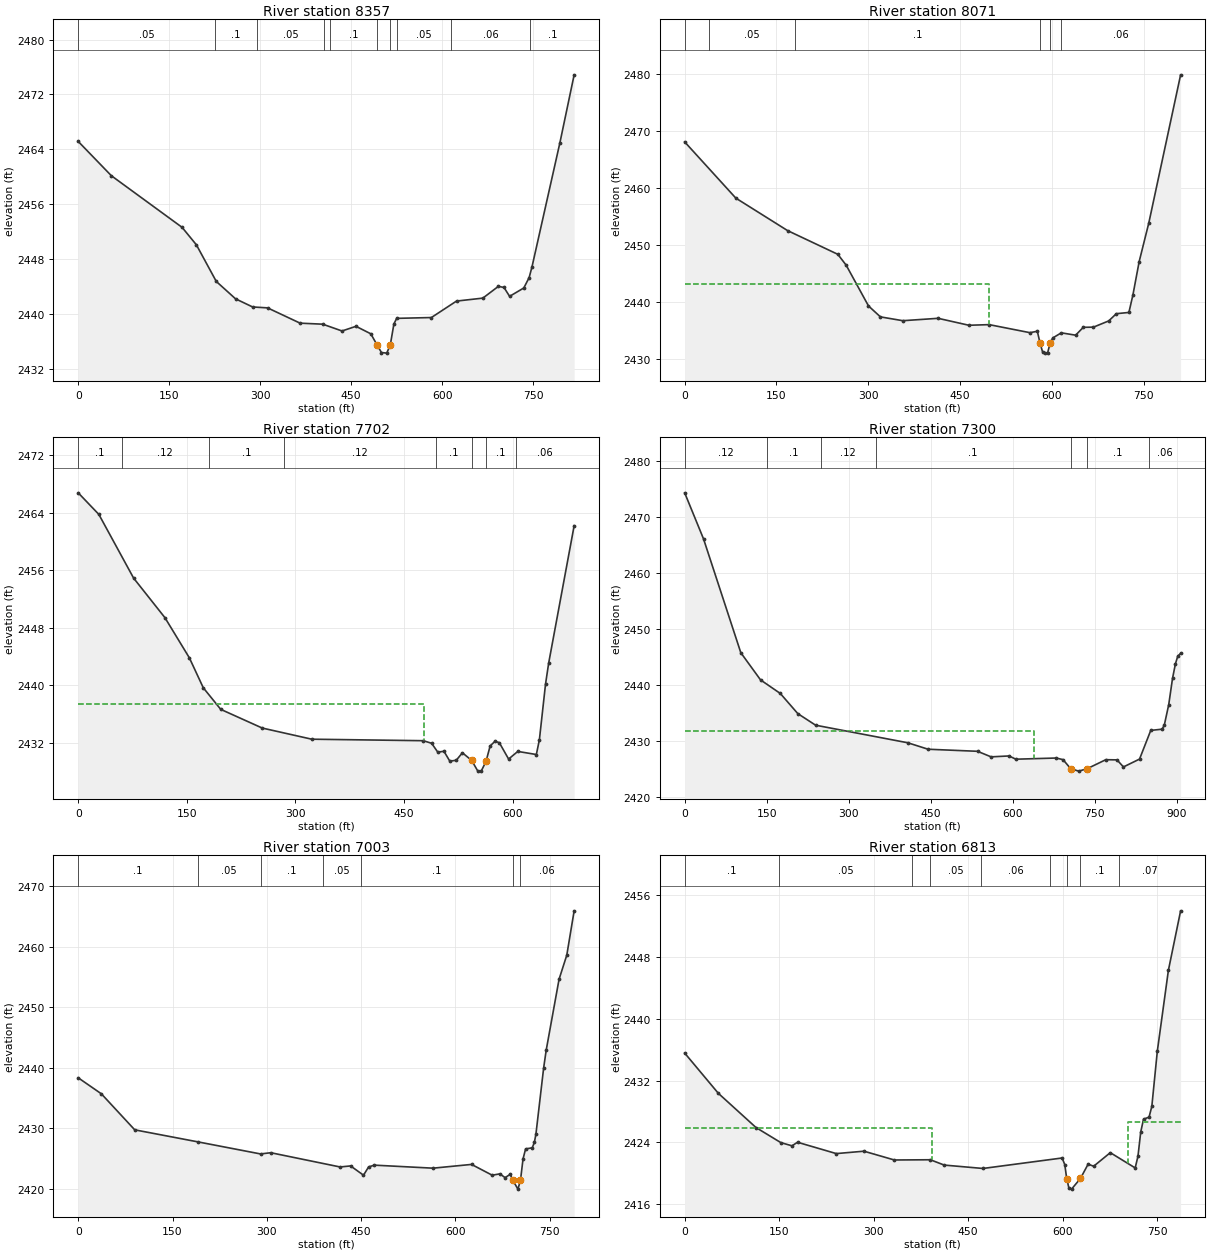
Type RM Length L Ch R = 1 ,8357    ,288.6,285.1,281.3
XS GIS Cut Line= 3
2236907.50961018417410.118887357 2236781.2792427417531.674056048
2236463.36572458418089.581112347
#Sta/Elev= 30
       0 2465.15    54.6 2460.15   171.2 2452.62   194.8 2450.07   227.6 2444.73
   259.3  2442.2   287.5 2441.01   312.1 2440.88   365.7 2438.65     403  2438.5
   434.8 2437.51   457.8 2438.19   482.2  2437.1   492.6 2435.47   499.8 2434.37
   508.5 2434.28   514.4 2435.49   520.3 2438.53   524.9 2439.35   582.1 2439.47
   623.5 2441.87   666.9  2442.3   692.6 2444.02   701.8 2443.85     711 2442.56
   734.4 2443.78   743.2 2445.29   747.9 2446.85   793.9 2464.95   817.4 2474.86
#Mann= 10 ,-1,0
       0     .05       0  225.24      .1       0  295.24     .05       0
  405.24     .07       0  415.24      .1       0   492.6    .045       0
   514.4      .1       0  525.24     .05       0  615.24     .06       0
  745.24      .1       0
Bank Sta=492.6,514.4
XS Rating Curve= 0 ,0
Exp/Cntr(USF)=0,0
Exp/Cntr=0.3,0.1

Type RM Length L Ch R = 1 ,8071    ,367.9,369.4,370
XS GIS Cut Line= 3
2236642.60115545417213.7878532742236442.51034279417415.802616056
2236301.33088286417922.340204105
#Sta/Elev= 30
       0 2468.04    83.6 2458.17     168 2452.48   250.2 2448.31   263.8 2446.41
   300.3 2439.25   319.8 2437.33   356.4 2436.66     414 2437.08   464.3 2435.86
   497.5 2435.97     564 2434.56   576.1 2434.81   580.6 2432.71   584.7 2431.18
   588.9 2430.97     593 2431.06   597.2 2432.79   601.4 2433.64   615.3 2434.53
   638.7 2434.12   651.2  2435.5   667.8 2435.53   692.7 2436.62   705.2 2437.89
   725.7 2438.11   732.2 2441.14   742.5 2447.04   758.2  2453.8   810.2 2479.81
#Mann= 6 ,-1,0
       0      .1       0      40     .05       0     180      .1       0
   580.6    .045       0   597.2      .1       0  614.33     .06       0
#XS Ineff= 2 , 0
          497.89 2443.14
Permanent Ineff=
       F       F
Bank Sta=580.6,597.2
XS Rating Curve= 0 ,0
Exp/Cntr(USF)=0,0
Exp/Cntr=0.3,0.1

Type RM Length L Ch R = 1 ,7702    ,410.8,402.3,392.6
XS GIS Cut Line= 3
2236256.18744715417093.5102162712236137.21728495417271.790201664
2235977.47631059417714.345643418
#Sta/Elev= 30
       0 2466.74    28.5 2463.74    76.5 2454.88   119.8 2449.37   153.5 2443.79
   172.7 2439.63   196.8 2436.63   254.1 2434.03   322.5 2432.48   476.6 2432.27
     488 2431.91   496.5 2430.68     505  2430.8   513.1 2429.43     522 2429.55
   530.5 2430.59   543.3 2429.53   551.8 2428.04   556.8 2428.11   563.1 2429.39
   568.8 2431.54   575.6  2432.2   581.5 2431.99   594.3 2429.72     607 2430.78
   632.6 2430.35   636.8  2432.4   645.3 2440.16   649.6 2443.05   684.8 2462.17
#Mann= 8 ,-1,0
       0      .1       0      60     .12       0     180      .1       0
  284.33     .12       0  494.33      .1       0   543.3    .045       0
   563.1      .1       0  604.33     .06       0
#XS Ineff= 2 , 0
          477.24 2437.36
Permanent Ineff=
       F       F
Bank Sta=543.3,563.1
XS Rating Curve= 0 ,0
Exp/Cntr=0.3,0.1

Type RM Length L Ch R = 1 ,7300    ,299,296.9,294.8
XS GIS Cut Line= 3
2235523.32447064416898.7970817842235537.96252936417117.389363653
2235696.85842087417786.284309592
#Sta/Elev= 30
       0 2474.24    34.5    2466   102.6 2445.69   138.7 2440.83   174.8 2438.41
   206.8 2434.81   239.4 2432.74     408  2429.6     445 2428.45   535.4 2428.08
   560.1 2427.09     593 2427.25   605.3 2426.67   679.3 2426.88   691.7 2426.59
   705.8 2424.96   720.4 2424.54   735.7 2424.97   769.8 2426.58   790.3 2426.55
   802.1 2425.29   831.5 2426.69     852 2431.81   872.6 2432.03   876.7 2432.72
   884.9 2436.43   891.8  2441.1   897.2 2443.74   901.3 2445.04   906.6 2445.58
#Mann= 7 ,-1,0
       0     .12       0     150      .1       0  249.08     .12       0
  349.08      .1       0   705.8    .045       0   735.7      .1       0
  849.08     .06       0
#XS Ineff= 2 , 0
          638.31 2431.79
Permanent Ineff=
       F       F
Bank Sta=705.8,735.7
XS Rating Curve= 0 ,0
Exp/Cntr=0.3,0.1

Type RM Length L Ch R = 1 ,7003    ,193.1,190,178.7
XS GIS Cut Line= 3
 2235420.6322613417053.1262831762235355.92194215417366.527240657
2235456.15949535417824.574793899
#Sta/Elev= 30
       0 2438.33    36.8 2435.69    89.9 2429.74     190 2427.76     290 2425.76
   306.4 2425.96   416.5 2423.61   433.3 2423.78   453.8 2422.25   461.9 2423.61
   470.9 2423.91   564.4 2423.41   625.7 2424.03   658.5 2422.25   670.8 2422.47
     679 2421.85   687.2 2422.39   691.2 2421.45   699.4 2419.95   703.5 2421.38
   707.6 2424.95   711.7 2426.59   722.2 2426.77   725.6 2427.66   728.1 2429.03
   740.4 2439.98   744.5 2442.93   764.9  2454.6   777.2 2458.59   788.9  2465.9
#Mann= 7 ,-1,0
       0      .1       0     190     .05       0     290      .1       0
  390.01     .05       0  450.01      .1       0   691.2    .045       0
   703.5     .06       0
Bank Sta=691.2,703.5
XS Rating Curve= 0 ,0
Exp/Cntr(USF)=0,0
Exp/Cntr=0.3,0.1

Type RM Length L Ch R = 1 ,6813    ,72.9,73,73
BEGIN DESCRIPTION:
structure xs 4
END DESCRIPTION:
XS GIS Cut Line= 2
2235028.50763165417110.1393054812235353.90146784417826.847280877
#Sta/Elev= 30
       0 2435.56    53.4 2430.34   113.2  2425.9   152.7 2423.94   170.3 2423.53
   179.1 2423.99   240.6 2422.52   284.5 2422.83   332.8 2421.69   389.9 2421.72
   411.9 2421.03   473.4 2420.59   599.1 2421.95   603.3 2421.07   606.3 2419.28
   609.6 2418.12     614 2417.91   628.1 2419.29   640.3 2421.15   649.1 2420.88
   675.5 2422.64     715 2420.66   719.4 2422.17   723.8 2425.32   728.2 2426.98
     737 2427.25   741.4 2428.64   750.1 2435.79   767.7 2446.29   787.1 2454.01
#Mann= 9 ,-1,0
       0      .1       0     150     .05       0     360     .06       0
     390     .05       0     470     .06       0     580      .1       0
   606.3    .045       0   628.1      .1       0     690     .07       0
#XS Ineff= 2 , 0
          391.85  2425.9     704         2426.62
Permanent Ineff=
       F       F
Bank Sta=606.3,628.1
XS Rating Curve= 0 ,0
Exp/Cntr(USF)=0,0
Exp/Cntr=0.5,0.3

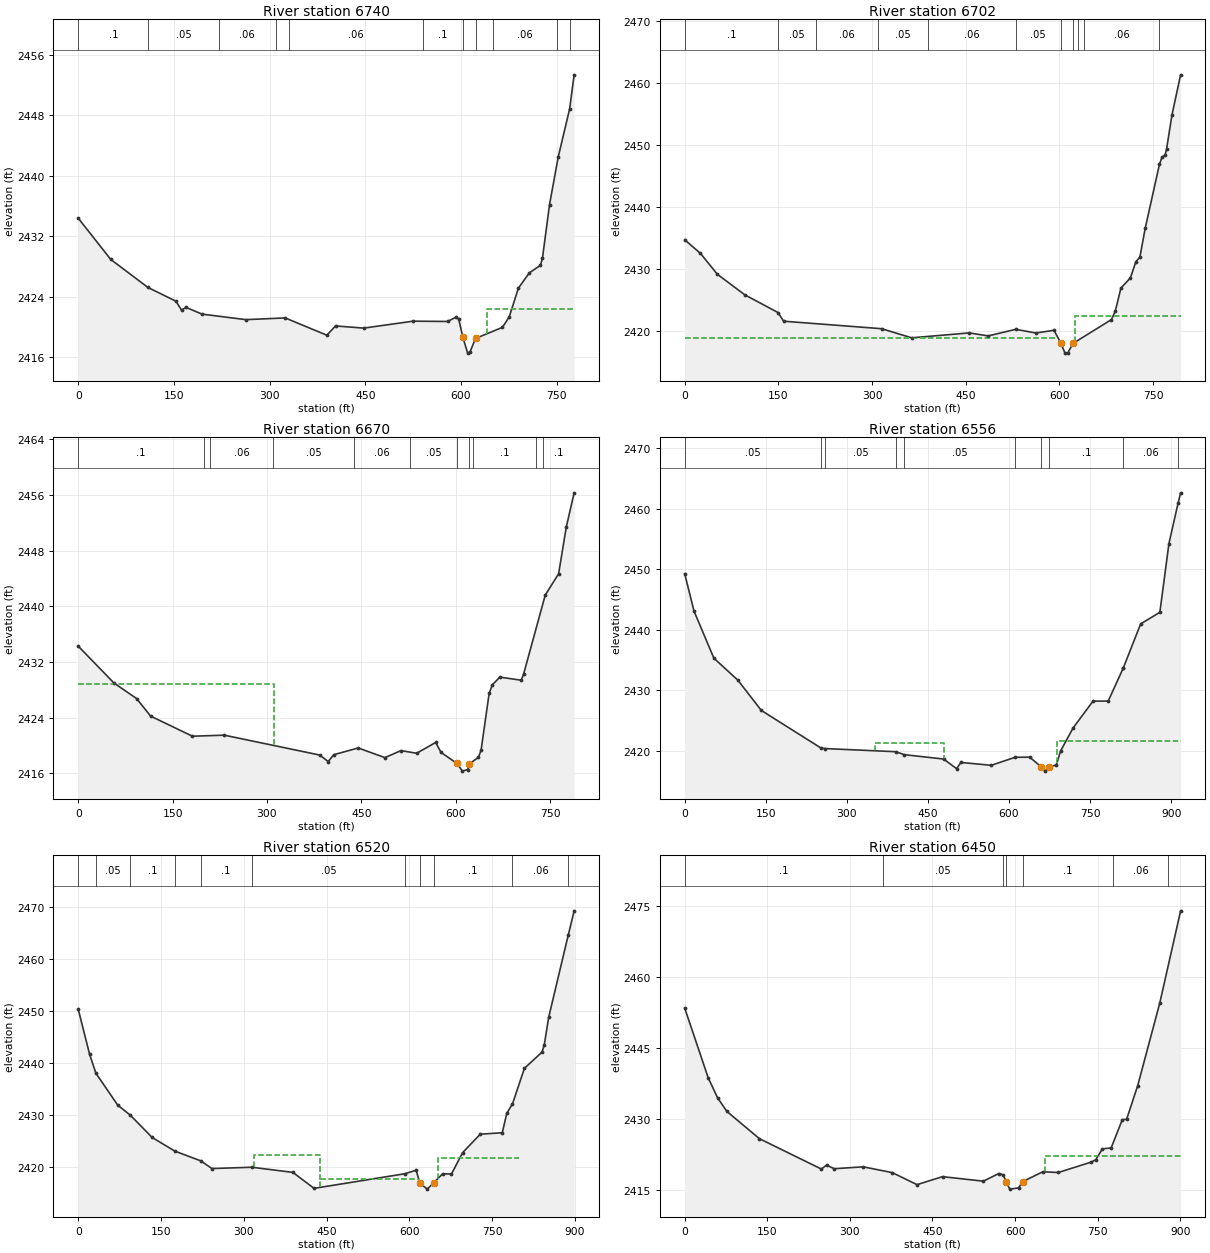
Type RM Length L Ch R = 1 ,6740    ,37.7,37.6,37.8
BEGIN DESCRIPTION:
structure xs 3
END DESCRIPTION:
XS GIS Cut Line= 3
2234964.27574469417141.5814622342235231.93269066417734.695302072
2235305.72508266417837.557424254
#Sta/Elev= 30
       0  2434.4      51 2428.94   109.3 2425.23   153.2 2423.41   161.9 2422.23
     169 2422.59   194.2  2421.7   262.9 2420.97   324.3  2421.2   389.7 2418.91
   403.3 2420.14   447.3 2419.85   524.9 2420.77   578.8 2420.73   592.3  2421.3
   596.4 2421.06   602.7 2418.69   610.4 2416.54   613.9 2416.66   622.7 2418.48
   664.9 2419.95   675.6 2421.34   689.9 2425.14   707.1 2427.17   724.3 2428.15
   727.6 2429.08   738.7 2436.19   752.2 2442.44   770.2 2448.86   777.3 2453.37
#Mann= 11 ,-1,0
       0      .1       0     110     .05       0     220     .06       0
     310     .05       0     330     .06       0     540      .1       0
   602.7    .045       0   622.7      .1       0     650     .06       0
  750.71     .07       0  770.71      .1       0
#XS Ineff= 2 , 0
          596.84  2418.8  640.88          2422.4
Permanent Ineff=
       F       F
Bank Sta=602.7,622.7
XS Rating Curve= 0 ,0
Exp/Cntr(USF)=0,0
Exp/Cntr=0.5,0.3

Type RM Length L Ch R = 1 ,6702    ,31.9,32.6,33.9
BEGIN DESCRIPTION:
structure xs 2
END DESCRIPTION:
XS GIS Cut Line= 3
2234930.54712505417153.401013624 2235196.0340863417746.695597091
2235283.92119418417860.916388848
#Sta/Elev= 30
       0 2434.66    25.3 2432.47    52.3  2429.1    96.2 2425.79   149.4 2422.93
   158.5 2421.53   315.3 2420.32   363.5 2418.85   455.5 2419.64   486.2 2419.16
     530 2420.22   562.2 2419.63   591.4 2420.06  602.332417.982   608.9 2416.41
   613.3 2416.38   621.7 2417.94   683.4  2421.8   689.6 2423.19   698.5 2426.87
   713.7 2428.51   722.4 2431.11   728.9 2431.87   737.4 2436.52   760.2 2446.83
   764.2 2447.97   769.2 2448.32   771.7 2449.34   780.2 2454.78   794.1 2461.27
#Mann= 11 ,-1,0
       0      .1       0     150     .05       0     210     .06       0
     310     .05       0     390     .06       0     530     .05       0
  602.33    .045       0   621.7     .05       0     630      .1       0
     640     .06       0  759.99      .1       0
#XS Ineff= 2 , 0
          598.27  2418.8  625.72          2422.4
Permanent Ineff=
       F       F
Bank Sta=602.33,621.7
XS Rating Curve= 0 ,0
Exp/Cntr=0.5,0.3

Type RM Length L Ch R = 1 ,6670    ,101.8,113.4,111.7
BEGIN DESCRIPTION:
structure xs 4/1
END DESCRIPTION:
XS GIS Cut Line= 3
2234895.24169304417162.4053784872235083.40286058417535.829090303
2235207.87223652417884.458664505
#Sta/Elev= 30
       0 2434.28    56.9 2428.97    92.7 2426.75   115.1 2424.22   181.5 2421.33
   232.1 2421.48     384 2418.62   397.3 2417.68   406.2 2418.67   445.1 2419.64
   487.5 2418.25     513 2419.26     538 2418.88   568.2 2420.43   576.7    2419
   602.2 2417.41   610.7 2416.31   619.2 2416.54  621.922417.375   636.2 2418.29
   640.4 2419.34   653.2  2427.5   658.4 2428.74   670.3 2429.82   704.2 2429.38
   707.8 2430.21   742.4 2441.63   763.6 2444.68   775.8 2451.41   788.3 2456.32
#Mann= 11 ,-1,0
       0      .1       0     200     .05       0     210     .06       0
     310     .05       0  438.15     .06       0  528.15     .05       0
   602.2    .045       0  621.92     .05       0  628.15      .1       0
  728.15     .06       0  738.15      .1       0
#XS Ineff= 2 , 0
          311.41 2428.88
Permanent Ineff=
       F       F
Bank Sta=602.2,621.92
XS Rating Curve= 0 ,0
Exp/Cntr(USF)=0,0
Exp/Cntr=0.5,0.3

Type RM Length L Ch R = 1 ,6556    ,40.3,36,36.6
BEGIN DESCRIPTION:
structure xs 3
END DESCRIPTION:
XS GIS Cut Line= 4
2234722.15787587417150.7674970482235037.20462006417472.610836261
2235049.96540623417712.7643576592235061.57730845417939.006014019
#Sta/Elev= 30
       0 2449.27    17.3 2443.08      54  2435.3    98.5 2431.65   141.7 2426.66
     252 2420.45   260.2 2420.35   390.6 2419.83   406.4 2419.34     479 2418.62
     503 2417.03     511 2418.06   567.1 2417.58   611.2 2418.91   638.2 2418.93
   659.1 2417.36   667.2 2416.62   674.3 2417.35   687.3 2417.62   695.3 2419.94
   718.5 2423.76   755.4  2428.2   783.4  2428.2   811.4 2433.68   811.4 2433.69
   843.5 2440.97     879 2442.88   895.8 2454.26   912.7 2460.94   917.4 2462.64
#Mann= 10 ,-1,0
       0     .05       0     252      .1       0   260.2     .05       0
   390.6     .06       0   406.4     .05       0   611.2      .1       0
   659.1    .045       0   674.3      .1       0   811.4     .06       0
   912.7      .1       0
#XS Ineff= 3 ,-1
  351.58     480 2421.26     480  654.09 2417.62   688.4   917.4  2421.6
Permanent Ineff=
       F       F       F
Bank Sta=659.1,674.3
XS Rating Curve= 0 ,0
Exp/Cntr(USF)=0,0
Exp/Cntr=0.5,0.3

Type RM Length L Ch R = 1 ,6520    ,69.7,70.7,71.6
BEGIN DESCRIPTION:
structure xs 2
END DESCRIPTION:
XS GIS Cut Line= 4
 2234675.8734078417180.2212494612235006.26175886417516.962213894
2235014.57248797417721.1690129572235020.90307893417943.213692935
#Sta/Elev= 30
       0 2450.32    20.7 2441.59      32 2437.99    71.6 2431.84    94.2 2429.93
   133.8 2425.63   175.1 2422.99   221.5 2421.14   242.3 2419.64   314.6 2419.89
   388.8  2418.9   427.2 2415.83   592.1 2418.65   612.1 2419.33  618.612416.876
   632.1 2415.68   644.1 2416.92   660.1 2418.63   676.1 2418.58   696.1 2422.68
   728.2 2426.25   768.2 2426.53   776.2 2430.26   786.6 2432.07   808.2 2438.92
   840.2 2442.06   844.2 2443.46   852.2 2448.76   887.8 2464.64   898.3 2469.23
#Mann= 11 ,-1,0
       0      .1       0      32     .05       0    94.2      .1       0
   175.1     .05       0   221.5      .1       0   314.6     .05       0
   592.1      .1       0  618.61    .045       0   644.1      .1       0
   786.6     .06       0   887.8      .1       0
#XS Ineff= 3 ,-1
  317.89  437.89 2422.33  437.89     617  2417.6   651.1   798.1  2421.6
Permanent Ineff=
       F       F       F
Bank Sta=618.61,644.1
XS Rating Curve= 0 ,0
Exp/Cntr(USF)=0,0
Exp/Cntr=0.5,0.3

Type RM Length L Ch R = 1 ,6450    ,145.8,143.6,141.1
BEGIN DESCRIPTION:
structure xs 4/1
END DESCRIPTION:
XS GIS Cut Line= 3
2234639.08794498 417190.028357962234951.50810451417496.768150952
2234932.19485829417959.149987055
#Sta/Elev= 30
       0 2453.41    42.6 2438.67    59.6 2434.44    76.5 2431.54   135.8 2425.75
   248.2 2419.33   257.6 2420.16   271.7  2419.4   324.2  2419.8   377.1 2418.57
   421.9 2416.03   468.3 2417.72   542.3 2416.76   570.4 2418.38   578.4 2418.11
   583.6 2416.66   590.4 2415.08   606.4 2415.34   613.5 2416.65   650.4 2418.75
   678.5  2418.6   738.5 2420.81   746.5  2421.3   758.5 2423.59   774.5 2423.81
   794.6 2429.76   802.6 2429.88   822.6 2436.95   862.6 2454.39   900.6 2473.97
#Mann= 7 ,-1,0
       0      .1       0     360     .05       0  577.83      .1       0
   583.6    .045       0   613.5      .1       0  777.83     .06       0
  877.83      .1       0
#XS Ineff= 2 , 0
                          655.19         2422.01
Permanent Ineff=
       F       F
Bank Sta=583.6,613.5
XS Rating Curve= 0 ,0
Exp/Cntr(USF)=0,0
Exp/Cntr=0.5,0.3

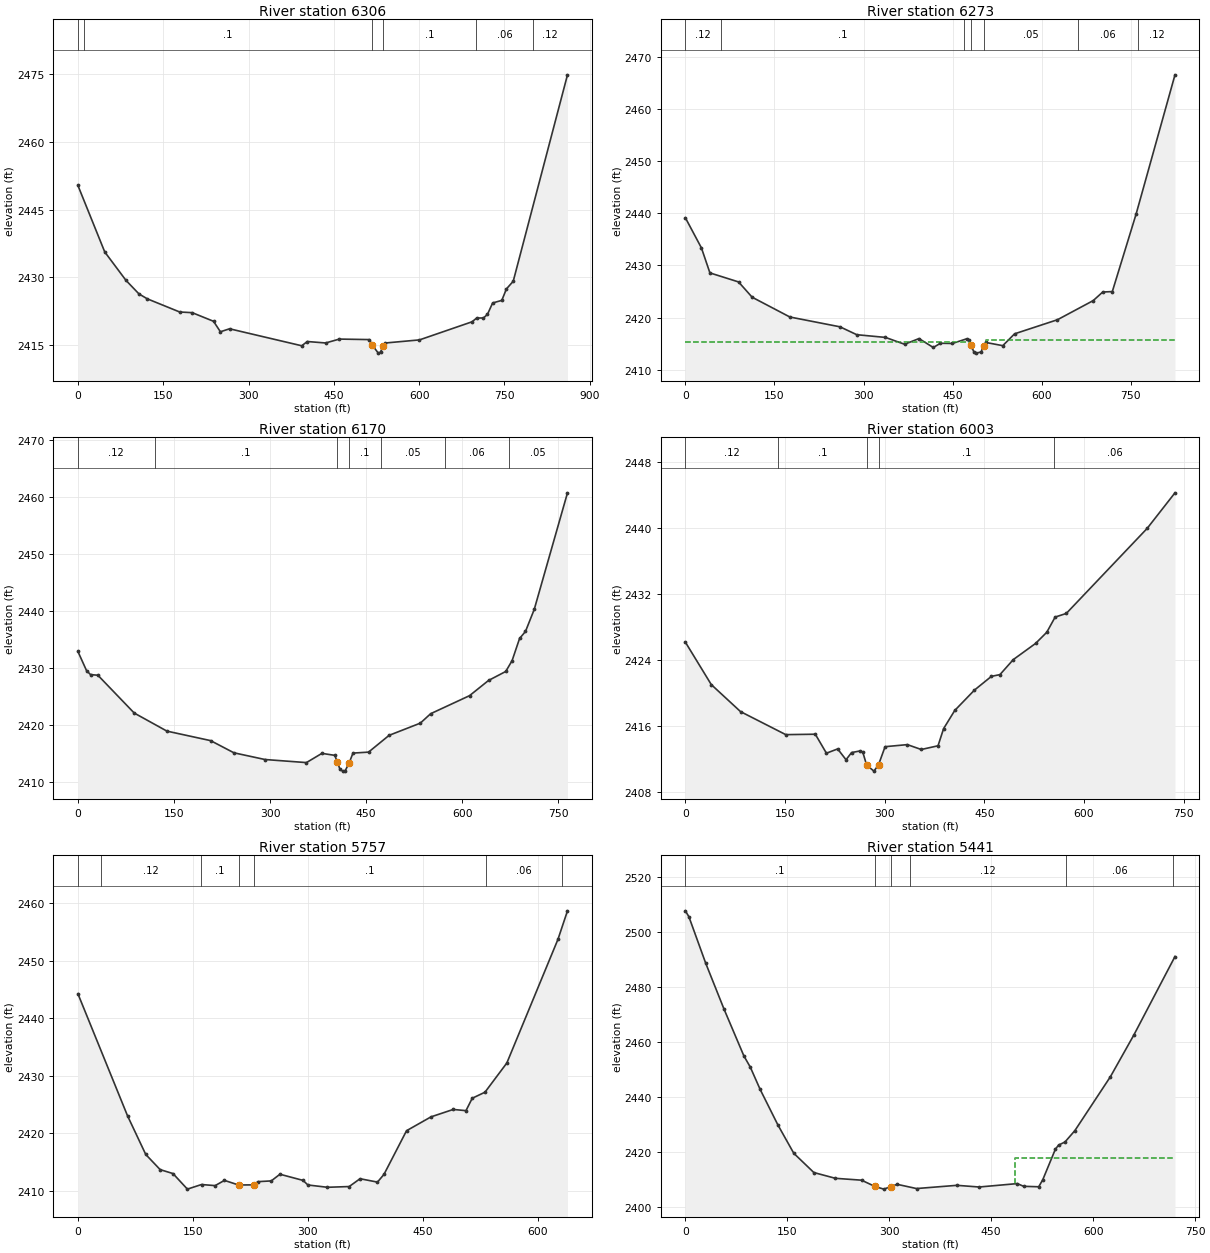
Type RM Length L Ch R = 1 ,6306    ,33.5,33.2,33.1
BEGIN DESCRIPTION:
structure xs 3
END DESCRIPTION:
XS GIS Cut Line= 3
2234593.12238911417222.2980386232234771.85626107417351.068938122
2234840.27728445417988.007405619
#Sta/Elev= 30
       0 2450.36    47.2 2435.63    84.5 2429.34   107.4 2426.33   122.1 2425.24
     179 2422.33     201 2422.18   238.5 2420.27   250.6 2417.95   266.7 2418.61
   393.6 2414.85   403.4 2415.79   435.6 2415.47   459.8 2416.33   512.1 2416.22
  517.882414.955   528.2 2413.22   532.2 2413.45   536.2 2414.73   540.2 2415.46
   600.6 2416.15   693.1 2420.16   701.2 2420.99   713.2 2421.01   720.2 2421.81
   729.3 2424.33   745.4  2424.9   753.5 2427.43   765.5 2429.14   860.9 2474.85
#Mann= 6 ,-1,0
       0     .12       0      10      .1       0  517.88    .045       0
   536.2      .1       0  700.29     .06       0  800.29     .12       0
#XS Ineff= 2 ,-1
       0  511.64  2415.3  542.63 860.893  2414.6
Permanent Ineff=
       F       F
Bank Sta=517.88,536.2
XS Rating Curve= 0 ,0
Exp/Cntr(USF)=0,0
Exp/Cntr=0.5,0.3

Type RM Length L Ch R = 1 ,6273    ,103.1,102.6,102.2
BEGIN DESCRIPTION:
structure xs 2
END DESCRIPTION:
XS GIS Cut Line= 4
 2234551.0282844417270.0370129942234741.01774702417398.435869366
2234776.19383104 417698.818095252234798.64066506417990.363938568
#Sta/Elev= 30
       0 2439.11      27 2433.34    41.3 2428.55    89.5 2426.82   112.4 2423.89
   175.9  2420.1   260.3 2418.22   288.5 2416.71   336.8 2416.19     369 2414.88
   393.3 2415.97   417.3 2414.26   429.4 2415.07   449.5 2415.03   473.7 2415.93
   477.7 2415.66  480.71 2414.68   485.8 2413.39   489.8 2413.18   497.9 2413.41
   501.9  2414.6   505.9 2415.22   534.3 2414.61   554.2 2416.88   626.4 2419.58
   686.5 2423.24   702.6 2424.89   718.7 2424.97   758.8 2439.84   824.2  2466.5
#Mann= 7 ,-1,0
       0     .12       0      60      .1       0  469.31     .05       0
  480.71    .045       0   501.9     .05       0  661.74     .06       0
  761.74     .12       0
#XS Ineff= 2 ,-1
       0  479.86  2415.3  505.84 824.152  2415.7
Permanent Ineff=
       F       F
Bank Sta=480.71,501.9
XS Rating Curve= 0 ,0
Exp/Cntr(USF)=0,0
Exp/Cntr=0.5,0.3

Type RM Length L Ch R = 1 ,6170    ,168.5,167.1,164.1
BEGIN DESCRIPTION:
structure xs 1
END DESCRIPTION:
XS GIS Cut Line= 4
2234508.96881079417320.4772133352234633.79661863 417425.66918624
2234708.13227949417934.7983351022234750.20906865418010.536555594
#Sta/Elev= 30
       0 2432.92    13.5 2429.55    19.7 2428.85    31.2 2428.74    87.9  2422.1
     139 2418.92   207.2 2417.25   243.6 2415.11   292.1 2413.93   356.8 2413.39
     381 2415.01   401.2 2414.66   404.8 2413.51   409.3  2412.2   413.4 2411.89
   417.4 2411.97  423.522413.342   429.5 2415.06   453.8 2415.23   485.9 2418.18
   534.6 2420.32   550.8 2421.98   611.5 2425.15   641.1 2427.82     668  2429.4
   677.9  2431.3   689.6  2435.2   698.8 2436.43   712.5 2440.31   764.4 2460.79
#Mann= 7 ,-1,0
       0     .12       0     120      .1       0   404.8    .045       0
  423.52      .1       0  473.24     .05       0  573.24     .06       0
  673.24     .05       0
Bank Sta=404.8,423.52
XS Rating Curve= 0 ,0
Exp/Cntr(USF)=0,0
Exp/Cntr=0.3,0.1

Type RM Length L Ch R = 1 ,6003    ,250.9,245.8,238.7
XS GIS Cut Line= 3
2234467.05362842417398.2590470382234476.16676672417583.559525739
2234643.24096883418109.083834188
#Sta/Elev= 30
       0 2426.14      39    2421      83 2417.73   151.1 2414.94   195.6 2414.99
   212.3 2412.69   229.2 2413.21   241.8  2411.9   250.2 2412.77   263.3 2412.97
     267 2412.83   272.8 2411.26   283.8 2410.52  290.712411.282   300.6 2413.48
   334.1 2413.73   355.1 2413.14   380.3 2413.59   388.7 2415.67   405.5 2417.87
   435.2 2420.34   460.7    2422   473.5 2422.21   493.6 2424.03   527.2 2425.99
     544 2427.34   556.6 2429.18   573.4 2429.62   695.1 2439.92     737 2444.23
#Mann= 5 ,-1,0
       0     .12       0     140      .1       0   272.8    .045       0
  290.71      .1       0  555.52     .06       0
Bank Sta=272.8,290.71
XS Rating Curve= 0 ,0
Exp/Cntr(USF)=0,0
Exp/Cntr=0.3,0.1

Type RM Length L Ch R = 1 ,5757    ,319.4,316,308.7
XS GIS Cut Line= 3
2234145.46774234417616.3907470552234438.41359748 417947.04130759
2234489.03874334418137.177021371
#Sta/Elev= 30
       0 2444.26    64.8    2423    88.5  2416.3   107.3 2413.66     124 2412.98
   142.8 2410.27   161.2 2411.07     179 2410.88   191.1 2411.79   209.5 2410.99
   229.2 2411.01   234.8 2411.57   252.2  2411.7   263.5 2412.86   293.6 2411.79
     300 2410.99   325.5 2410.59   353.8 2410.72     368 2412.08   390.7 2411.49
   399.2 2412.84   428.6 2420.43   460.5 2422.84   489.5 2424.13   506.1 2423.92
   514.3 2426.08   530.9 2427.13   559.4 2432.21   626.1 2453.73   638.5 2458.68
#Mann= 7 ,-1,0
       0      .1       0      30     .12       0     160      .1       0
   209.5    .045       0   229.2      .1       0  531.75     .06       0
  631.75      .1       0
Bank Sta=209.5,229.2
XS Rating Curve= 0 ,0
Exp/Cntr(USF)=0,0
Exp/Cntr=0.3,0.1

Type RM Length L Ch R = 1 ,5441    ,320.9,326.5,330.8
XS GIS Cut Line= 3
  2233826.511423417807.7169403452234320.32528758418106.998070392
2234395.14557009418228.848244768
#Sta/Elev= 30
       0 2507.64     5.2 2505.47      30 2488.54    56.8 2471.96    86.1 2454.91
    95.5 2450.86     110 2442.76   136.2 2429.81   159.5 2419.55     189 2412.56
   220.7 2410.46   259.2 2409.78   278.9  2407.5   291.9 2406.53   302.2 2407.41
   311.5 2408.28   340.1 2406.74   399.5 2407.91   432.3  2407.3   488.4 2408.54
   497.7 2407.55   519.9 2407.39   525.8 2409.91   544.5 2421.09   549.2 2422.54
   558.5 2423.65   573.1 2427.79   625.4 2447.38   659.8 2462.49   720.4 2491.04
#Mann= 6 ,-1,0
       0      .1       0   278.9    .045       0   302.2      .1       0
     330     .12       0     560     .06       0  717.43      .1       0
#XS Ineff= 2 , 0
                          485.39          2417.9
Permanent Ineff=
       F       F
Bank Sta=278.9,302.2
XS Rating Curve= 0 ,0
Exp/Cntr(USF)=0,0
Exp/Cntr=0.3,0.1