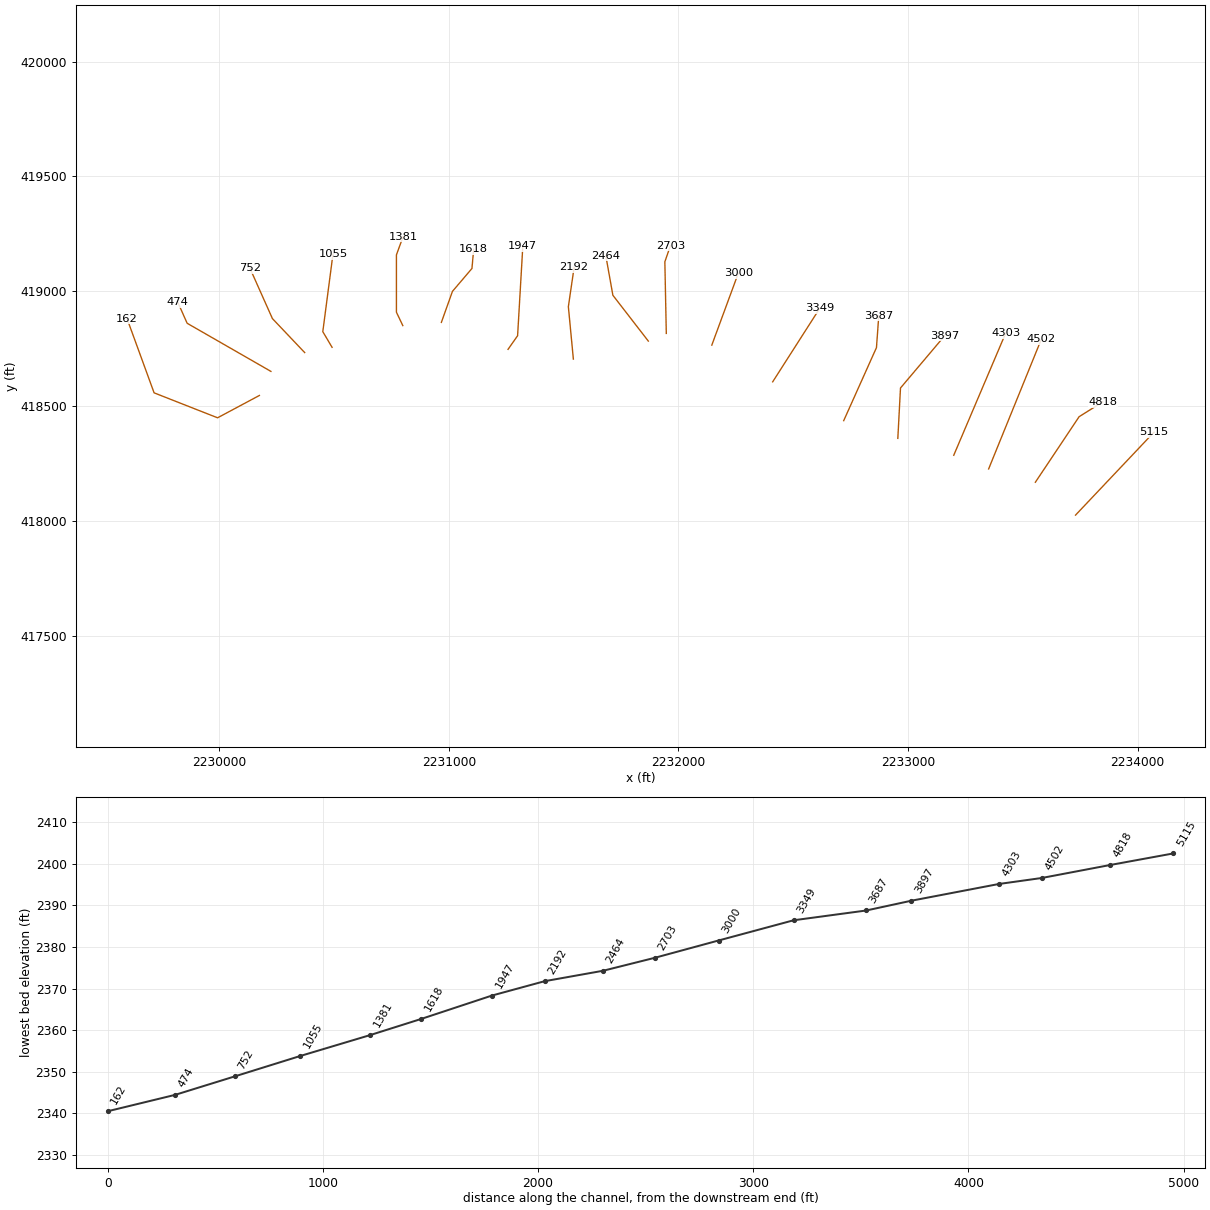
HEC-RAS study NFBEAVERCK.prj: NFBEAVERCK

--- NFBEAVERCK.g01 (geometry) --- (continued)

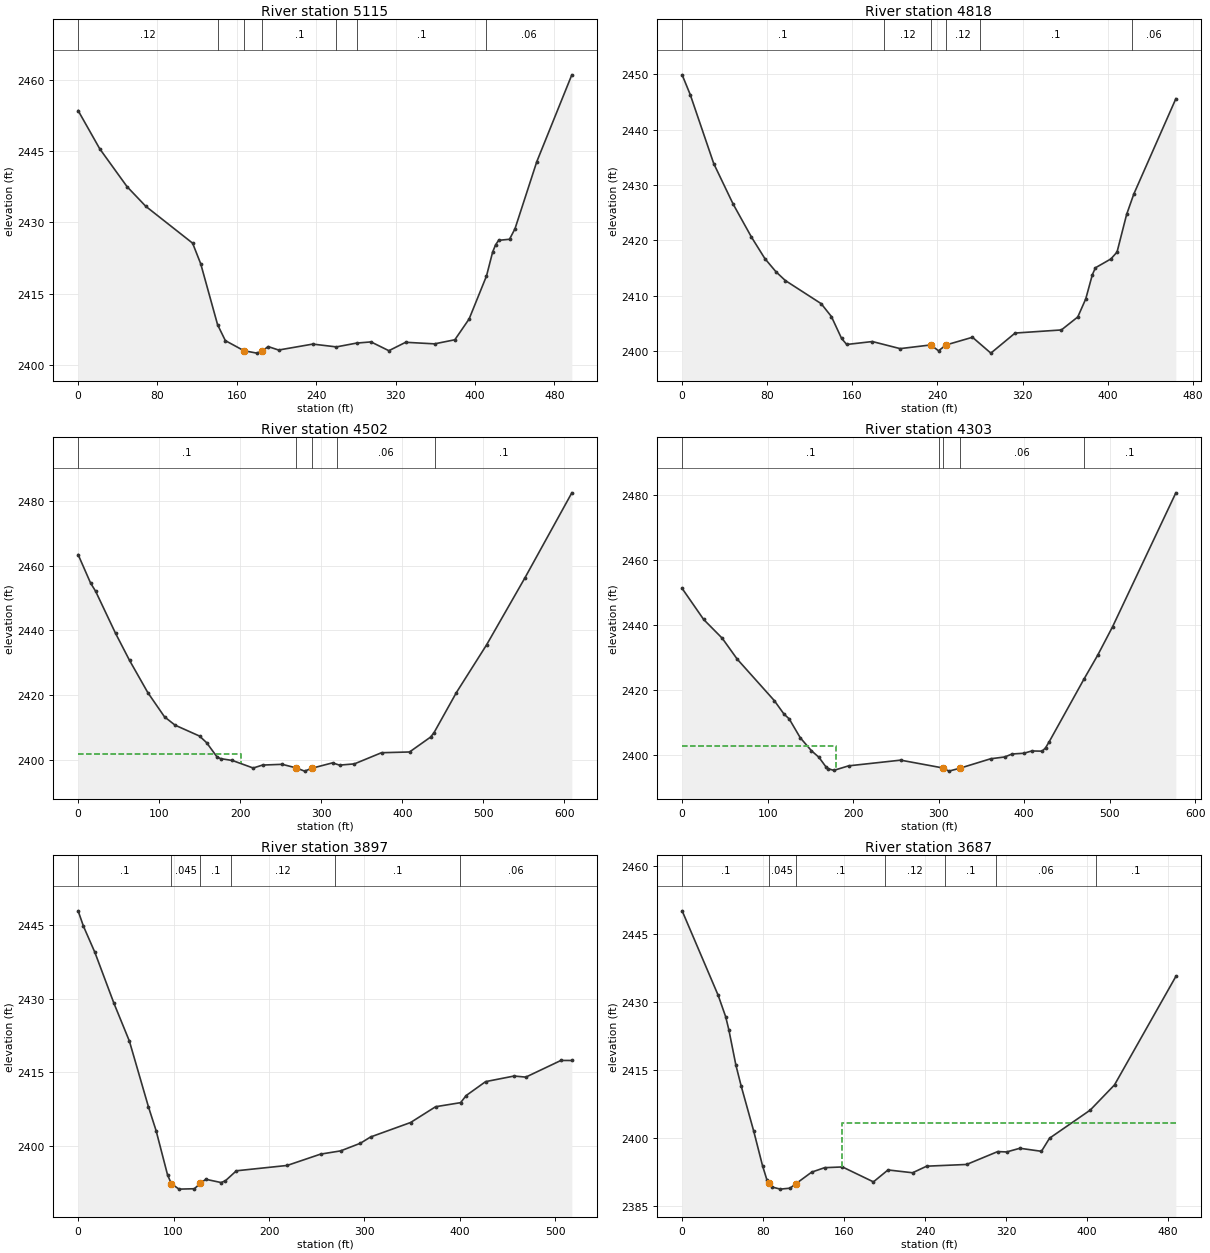
Type RM Length L Ch R = 1 ,5115    ,296.1,296.6,299.2
XS GIS Cut Line= 2
2233729.27367477418025.3804362552234071.31569983418386.789390658
#Sta/Elev= 30
       0  2453.5    21.8 2445.46    49.3 2437.51    68.2 2433.37   115.4 2425.62
   123.6 2421.27   140.6 2408.46   148.4 2405.13   167.2    2403   180.2  2402.5
   185.8 2402.96   191.5 2403.88   202.1 2403.15   236.5  2404.4   260.3 2403.81
   280.6 2404.61   295.2 2404.86   313.2 2403.01   330.1 2404.78   359.2 2404.45
   379.7 2405.31   394.1 2409.69   411.6 2418.72   417.8 2423.76   420.7 2425.25
   423.8 2426.21   434.8 2426.44   440.3 2428.64   462.3 2442.76   497.6 2461.01
#Mann= 7 ,-1,0
       0     .12       0   140.6      .1       0   167.2    .045       0
   185.8      .1       0   260.3     .12       0   280.6      .1       0
   411.6     .06       0
Bank Sta=167.2,185.8
XS Rating Curve= 0 ,0
Exp/Cntr(USF)=0,0
Exp/Cntr=0.3,0.1

Type RM Length L Ch R = 1 ,4818    ,312,315.8,316.5
XS GIS Cut Line= 3
2233554.37612556418168.4996089262233745.01386774418454.039982585
2233847.40881223418518.140882794
#Sta/Elev= 30
       0 2449.87     7.6 2446.31    29.7 2433.87    47.9 2426.58    65.2  2420.6
    77.8 2416.73    88.3 2414.34      97 2412.78   130.7 2408.61   140.3 2406.29
   149.9 2402.33   154.7 2401.25   178.8 2401.78   204.9  2400.5   233.8 2401.17
     241 2400.11   248.2 2401.17   272.9 2402.55   290.2 2399.69     313 2403.31
   356.5 2403.87   371.9 2406.21   379.4 2409.47   385.6 2413.83   388.5 2415.08
     403 2416.67   408.8 2417.91   417.8 2424.69   424.6 2428.39   464.1 2445.57
#Mann= 6 ,-1,0
       0      .1       0     190     .12       0   233.8    .045       0
   248.2     .12       0     280      .1       0  423.33     .06       0
Bank Sta=233.8,248.2
XS Rating Curve= 0 ,0
Exp/Cntr(USF)=0,0
Exp/Cntr=0.3,0.1

Type RM Length L Ch R = 1 ,4502    ,196.7,199.1,195.6
XS GIS Cut Line= 2
2233350.86385702418226.3790102762233580.17865445418790.710179076
#Sta/Elev= 30
       0 2463.41    15.4 2454.62    21.6  2452.1    46.2 2439.11    63.5 2430.74
      86 2420.82   106.6 2413.34   119.6 2410.78   149.8 2407.41   158.5 2405.38
   171.4 2400.97   175.7 2400.45   190.4 2399.87     216 2397.55   227.5 2398.46
   251.8 2398.69   269.1 2397.58   279.4 2396.59   288.7  2397.5   313.9 2399.14
   322.5 2398.44   340.9 2398.83   374.3 2402.27   408.9  2402.5   434.8 2407.09
   439.1 2408.46   466.7 2420.84   503.9 2435.54   551.4  2456.3   609.1 2482.46
#Mann= 5 ,-1,0
       0      .1       0   269.1    .045       0   288.7      .1       0
     320     .06       0     440      .1       0
#XS Ineff= 2 , 0
          200.41 2401.95
Permanent Ineff=
       F       F
Bank Sta=269.1,288.7
XS Rating Curve= 0 ,0
Exp/Cntr=0.3,0.1

Type RM Length L Ch R = 1 ,4303    ,402,406.7,407
XS GIS Cut Line= 2
2233198.99157586 418285.959635272233424.95951765418817.373898392
#Sta/Elev= 30
       0 2451.23    25.2 2441.69      47 2435.91    64.4 2429.53   107.8  2416.8
   119.2 2412.64   125.2  2411.2   138.2 2405.38   151.3  2401.4     160  2399.4
     168 2396.54   171.1 2395.88   177.4 2395.38   194.7 2396.77   255.6 2398.52
   305.3 2396.11   312.1 2395.15   325.1 2396.06   360.8 2398.94   377.3  2399.5
     386 2400.41   399.8 2400.64     409 2401.34   421.2 2401.28   425.1 2402.32
   429.5 2404.24     470 2423.39     486  2430.7   503.4 2439.43   577.5 2480.57
#Mann= 5 ,-1,0
       0      .1       0     300     .06       0   305.3    .045       0
   325.1     .06       0     470      .1       0
#XS Ineff= 2 , 0
          180.13 2402.83
Permanent Ineff=
       F       F
Bank Sta=305.3,325.1
XS Rating Curve= 0 ,0
Exp/Cntr(USF)=0,0
Exp/Cntr=0.3,0.1

Type RM Length L Ch R = 1 ,3897    ,216.9,209.9,202.6
XS GIS Cut Line= 3
2232955.48118987418359.5867345262232967.07131375418578.901361684
2233159.23541077418806.114865146
#Sta/Elev= 30
       0  2447.9     5.6 2444.76    17.6 2439.41    37.6 2429.01    53.7 2421.34
    73.7 2407.91    81.7 2403.06    93.7 2394.04    97.7 2392.23   105.7 2391.13
   121.8 2391.21  128.16 2392.33   133.8 2393.14   149.8 2392.47   154.4 2392.85
   165.8 2394.87     219 2395.96     254 2398.27     275 2398.93   295.7 2400.49
   306.4 2401.77   348.3 2404.72   374.5 2407.94   400.7 2408.77   406.5 2410.22
   426.9 2413.06   456.7  2414.2     469 2413.98   505.8 2417.38   517.2 2417.37
#Mann= 6 ,-1,0
       0      .1       0    97.7    .045       0  128.16      .1       0
     160     .12       0  269.62      .1       0  399.62     .06       0
Bank Sta=97.7,128.16
XS Rating Curve= 0 ,0
Exp/Cntr(USF)=0,0
Exp/Cntr=0.3,0.1

Type RM Length L Ch R = 1 ,3687    ,340.6,337.3,335.1
XS GIS Cut Line= 3
2232719.79120479  418436.68755422232862.43152005418754.788080266
2232872.52994945418893.641484501
#Sta/Elev= 30
       0 2450.15    35.6 2431.52      43 2426.81    46.1 2423.97    53.1 2416.14
    58.2 2411.63    70.7 2401.59    79.4 2393.97    83.8 2390.79    85.4 2390.24
    88.9 2389.24      97 2388.78   106.6 2388.99   112.6    2390     128 2392.53
   140.8 2393.51   158.4 2393.67     189 2390.38   203.4 2393.01   227.7 2392.39
   241.6 2393.84   281.1 2394.22   311.8 2397.06   320.6 2396.98   333.7 2397.79
     355 2397.12     363 2400.01   403.2 2406.21   427.2 2411.77   487.8 2435.69
#Mann= 7 ,-1,0
       0      .1       0    85.4    .045       0   112.6      .1       0
     200     .12       0     260      .1       0     310     .06       0
  408.62      .1       0
#XS Ineff= 2 , 0
                          157.89          2403.4
Permanent Ineff=
       F       F
Bank Sta=85.4,112.6
XS Rating Curve= 0 ,0
Exp/Cntr(USF)=0,0
Exp/Cntr=0.3,0.1

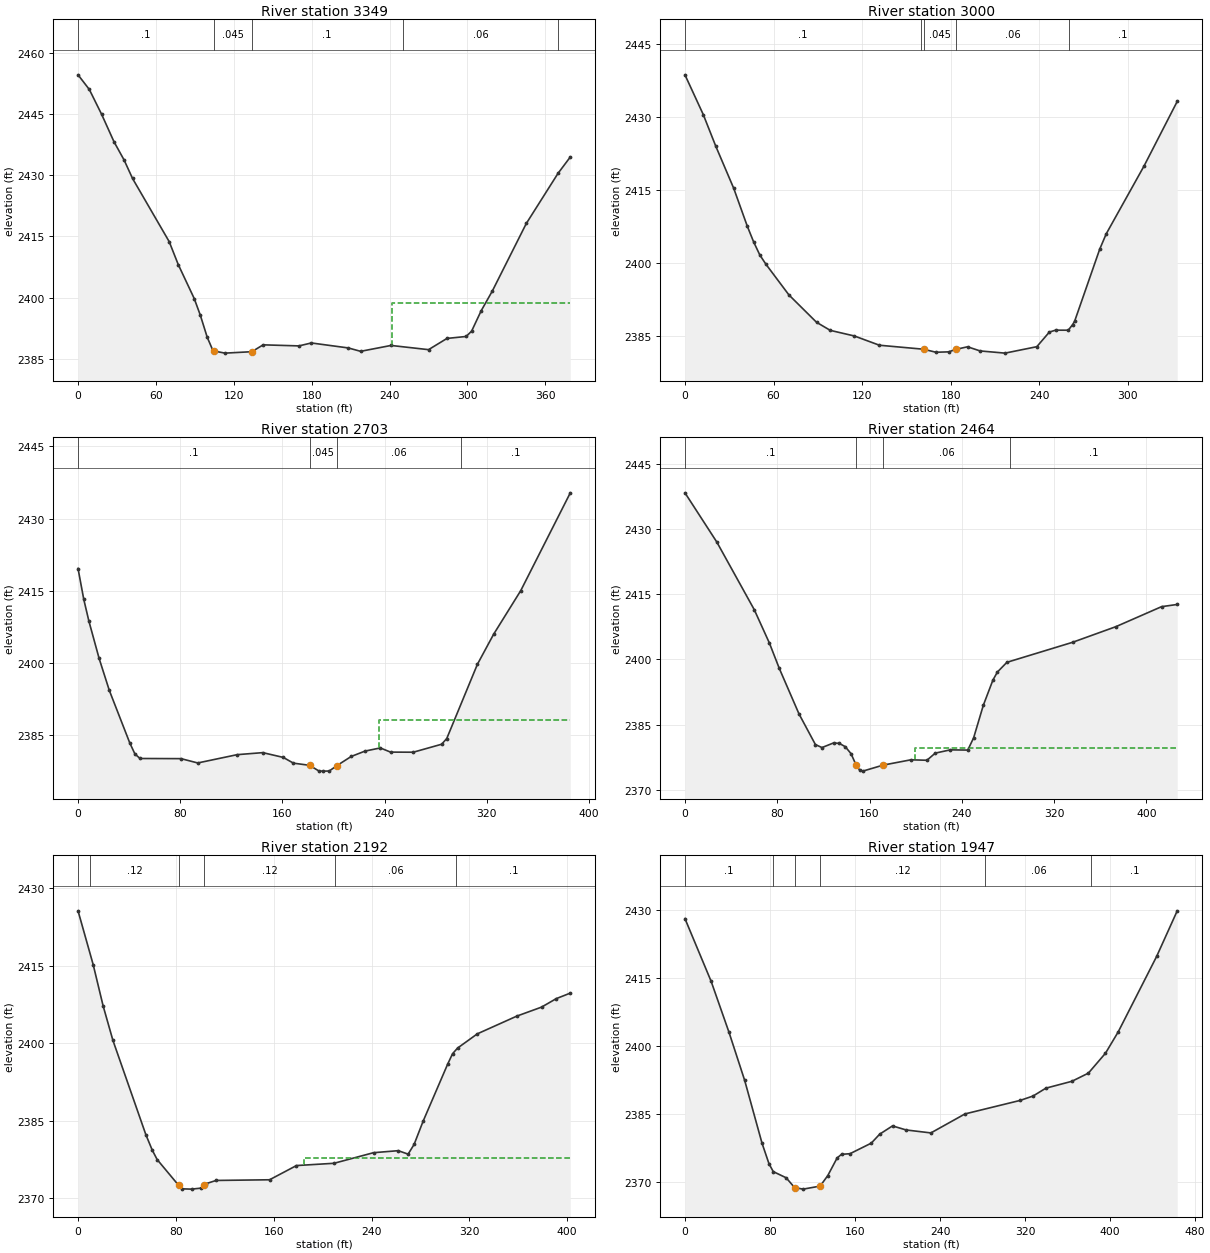
Type RM Length L Ch R = 1 ,3349    ,347.5,349,353.3
XS GIS Cut Line= 2
2232410.52680445418605.8362466322232615.01999978418925.199076373
#Sta/Elev= 30
       0 2454.59     8.7    2451    18.2  2444.9    27.7  2438.2    35.5 2433.72
      42  2429.2    70.2 2413.75    77.2 2408.12    89.5  2399.8    94.2 2395.72
    99.5 2390.33   103.7 2387.22     105 2386.93   113.2 2386.43   133.9 2386.78
   142.6 2388.46   170.2  2388.2   179.7 2388.92   208.2  2387.7   217.7 2386.87
   241.1 2388.31     270 2387.28   284.2 2390.03     299 2390.51   303.2 2391.83
   310.5 2396.78   319.2 2401.68   345.3 2418.18   369.7 2430.44   379.2 2434.47
#Mann= 5 ,-1,0
       0      .1       0     105    .045       0   133.9      .1       0
     250     .06       0     370      .1       0
#XS Ineff= 2 , 0
                          241.68         2398.66
Permanent Ineff=
       F       F
Bank Sta=105,133.9
XS Rating Curve= 0 ,0
Exp/Cntr(USF)=0,0
Exp/Cntr=0.3,0.1

Type RM Length L Ch R = 1 ,3000    ,288.9,297.1,299.6
XS GIS Cut Line= 2
2232145.41427928418765.5699617432232260.63605308419078.421656632
#Sta/Elev= 30
       0 2438.65    12.4  2430.5    20.9 2423.99      33 2415.39    42.2 2407.62
    46.5 2404.39    50.7  2401.7    54.8 2399.82    70.4 2393.51    89.1  2387.9
    98.4 2386.24   114.7 2385.09   131.7 2383.19   161.6 2382.37     170 2381.75
   178.6 2381.83   183.6 2382.35   191.4 2382.87   199.9 2382.02   216.8 2381.57
   238.3 2382.89   246.8 2385.89     251 2386.28   259.6 2386.27   262.6 2387.44
   263.9  2388.1   280.9 2402.89   285.3 2406.03   310.8 2419.88   333.4  2433.2
#Mann= 5 ,-1,0
       0      .1       0     160     .06       0   161.6    .045       0
   183.6     .06       0     260      .1       0
Bank Sta=161.6,183.6
XS Rating Curve= 0 ,0
Exp/Cntr(USF)=0,0
Exp/Cntr=0.3,0.1

Type RM Length L Ch R = 1 ,2703    ,225.8,239.3,246.7
XS GIS Cut Line= 3
2231947.26135578418816.640960334 2231940.9498374419128.429968026
2231964.93360723419197.856670143
#Sta/Elev= 30
       0 2419.59     4.5 2413.16     8.5 2408.64    16.5 2400.87    24.5  2394.2
    40.5 2383.27    44.5 2380.99    48.5 2380.03    80.6    2380    93.7  2379.1
   124.6 2380.83   144.6 2381.25   160.6 2380.26   168.6 2379.06   181.2 2378.61
   188.6 2377.42   191.8  2377.4   196.6 2377.42  202.632378.548   213.8 2380.45
   224.6 2381.57   236.6 2382.23   244.6 2381.36   262.4 2381.34   284.6    2383
   288.6 2384.19   312.6 2399.65   325.3 2405.91   346.5 2414.98   385.3 2435.35
#Mann= 4 ,-1,0
       0      .1       0   181.2    .045       0  202.63     .06       0
     300      .1       0
#XS Ineff= 2 , 0
                          235.42         2388.13
Permanent Ineff=
       F       F
Bank Sta=181.2,202.63
XS Rating Curve= 0 ,0
Exp/Cntr(USF)=0,0
Exp/Cntr=0.3,0.1

Type RM Length L Ch R = 1 ,2464    ,279.8,271.8,261.7
XS GIS Cut Line= 3
2231868.94296832418783.2594217022231714.64195112418982.673871898
2231683.91251126419154.627971575
#Sta/Elev= 30
       0  2438.3    27.6 2426.99    60.1 2411.42    73.2 2403.76    81.8 2397.91
    98.9 2387.44   113.1 2380.41   118.8 2379.72   128.9 2380.79   133.9 2380.67
     139 2379.92     144 2378.31  148.482375.636   151.6 2374.49   154.2  2374.3
   171.82375.682   195.8  2376.9   209.8  2376.8     217 2378.44     230 2379.19
   245.2 2379.14   250.3 2381.97   258.7 2389.46     267 2395.24   270.9 2397.09
   279.1 2399.32     336 2403.92   373.6 2407.52   413.2 2412.12   426.8 2412.63
#Mann= 4 ,-1,0
       0      .1       0  148.48    .045       0   171.8     .06       0
  282.14      .1       0
#XS Ineff= 2 , 0
                          199.83         2379.68
Permanent Ineff=
       F       F
Bank Sta=148.48,171.8
XS Rating Curve= 0 ,0
Exp/Cntr(USF)=0,0
Exp/Cntr=0.3,0.1

Type RM Length L Ch R = 1 ,2192    ,245.8,244.9,241.4
XS GIS Cut Line= 3
2231542.56389619418704.7875918562231520.73870987418933.011733594
2231545.84878717419104.446198203
#Sta/Elev= 30
       0 2425.64    12.4 2415.22    20.5 2407.26    28.5 2400.59    55.5  2382.3
    60.7 2379.33    64.7 2377.51    82.2 2372.54    84.8 2371.85    92.8 2371.79
   100.8 2371.99  103.35 2372.53   104.9 2372.86   112.9 2373.47   156.6  2373.6
   178.6 2376.35   209.3 2376.79   241.6 2378.84   261.8 2379.23   269.9 2378.56
   274.8 2380.45   282.2 2384.96   302.2 2395.96   306.2 2397.98   310.3 2399.08
   326.5 2401.84   358.8 2405.27     379 2407.01   391.1 2408.66   402.5 2409.72
#Mann= 6 ,-1,0
       0      .1       0      10     .12       0    82.2    .045       0
  103.35     .12       0     210     .06       0  309.27      .1       0
#XS Ineff= 2 , 0
                          184.85         2377.81
Permanent Ineff=
       F       F
Bank Sta=82.2,103.35
XS Rating Curve= 0 ,0
Exp/Cntr(USF)=0,0
Exp/Cntr=0.3,0.1

Type RM Length L Ch R = 1 ,1947    ,334.8,329.4,325.4
XS GIS Cut Line= 3
 2231258.0435493418747.2142582172231299.69957057418806.542530936
2231322.42103672419196.594366468
#Sta/Elev= 30
       0 2428.12    24.6 2414.28    41.5 2402.96    56.2 2392.36    72.5  2378.5
    79.1 2373.93    83.1 2372.21    95.2 2370.85   103.2 2368.68   111.2 2368.34
   127.2 2369.01   134.4 2371.34   143.2 2375.24   147.3 2376.03   155.3 2376.17
   175.3  2378.5   183.3  2380.5   195.3 2382.31     208 2381.42   231.4 2380.76
   263.5 2384.96   315.5 2387.95   327.6 2388.92   339.6 2390.65   364.1 2392.17
   379.6 2393.97   395.7 2398.38   407.7  2403.1   443.8 2419.75   463.2 2429.84
#Mann= 6 ,-1,0
       0      .1       0   82.49     .12       0   103.2    .045       0
   127.2     .12       0  282.49     .06       0  382.49      .1       0
Bank Sta=103.2,127.2
XS Rating Curve= 0 ,0
Exp/Cntr(USF)=0,0
Exp/Cntr=0.3,0.1

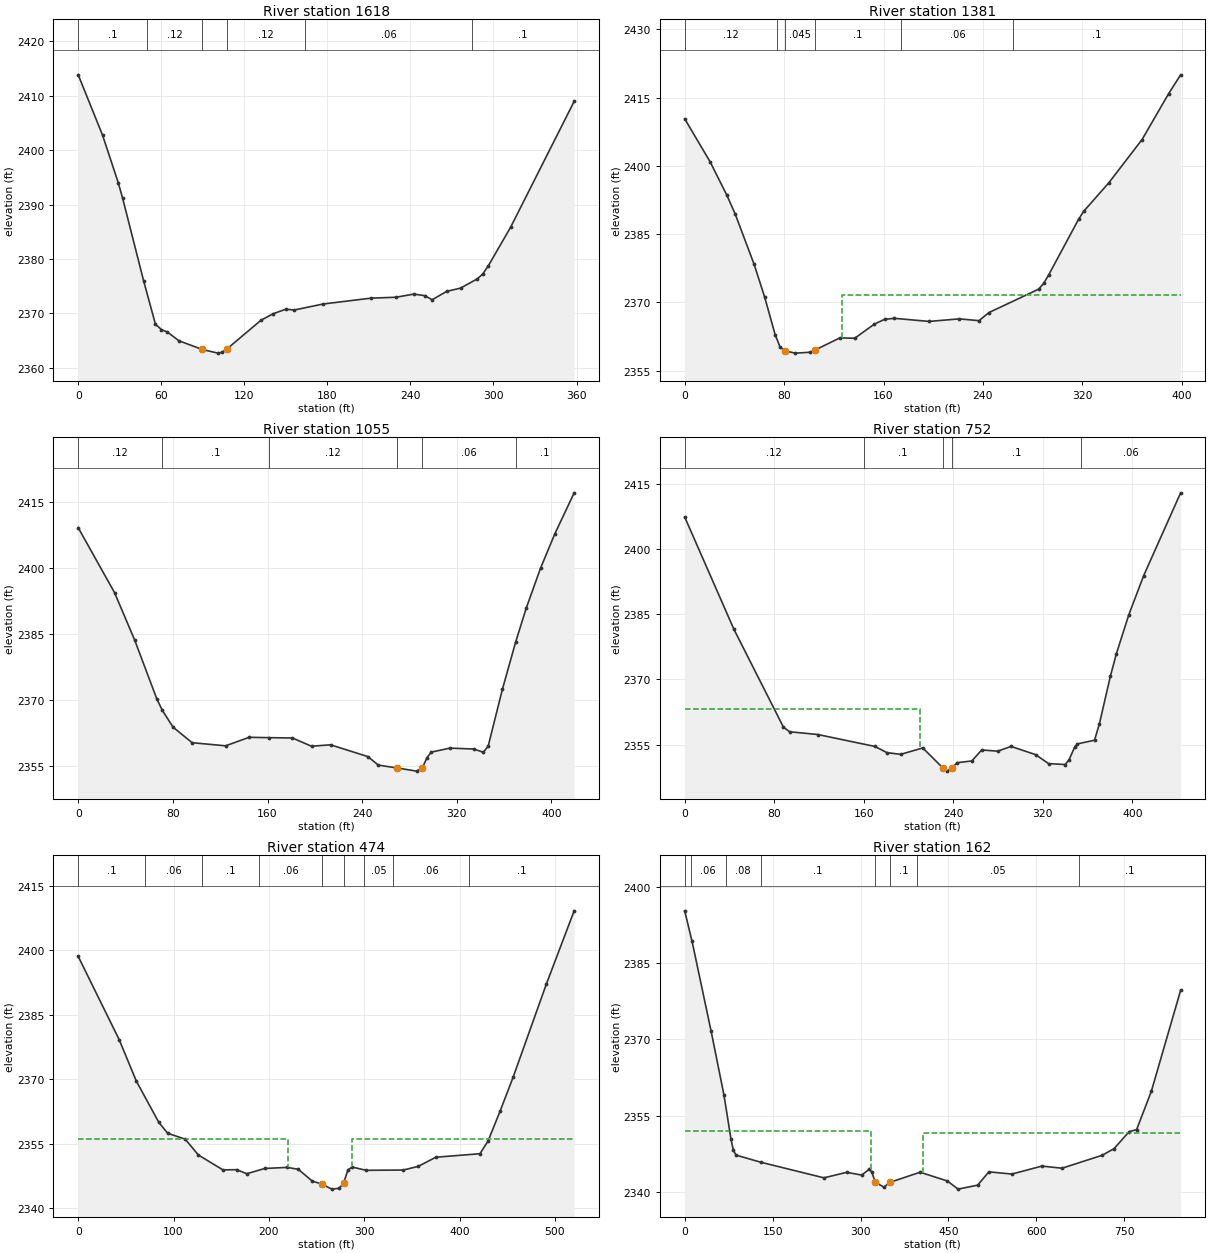
Type RM Length L Ch R = 1 ,1618    ,233.2,236.6,241.4
XS GIS Cut Line= 4
2230967.71370408418864.6084999792231016.07591689418999.830028385
2231100.96480012 419099.482195662231108.41908557419182.901206074
#Sta/Elev= 30
       0 2413.82    17.6 2402.73      29 2393.95    32.1 2391.15    47.3 2375.94
    55.8 2368.03    60.1 2367.03    64.3 2366.61    72.8 2364.97    89.72363.379
   100.9 2362.71   104.1 2362.88 107.3992363.468     132 2368.74   140.8 2369.94
   149.9 2370.77   156.1 2370.63   176.9 2371.73   211.6 2372.81   229.5 2372.97
   242.5 2373.55   250.5 2373.26   255.7 2372.51   266.2 2374.05   276.2 2374.65
   288.3 2376.34   292.3 2377.26   296.3 2378.75   312.4 2385.83   358.3 2408.94
#Mann= 6 ,-1,0
       0      .1       0      50     .12       0    89.7    .045       0
 107.399     .12       0  163.61     .06       0  284.52      .1       0
Bank Sta=89.7,107.399
XS Rating Curve= 0 ,0
Exp/Cntr(USF)=0,0
Exp/Cntr=0.3,0.1

Type RM Length L Ch R = 1 ,1381    ,329.7,326.5,325.1
XS GIS Cut Line= 4
2230799.82731533418850.7231595562230772.05663448  418908.7891286
2230772.05663448419158.725256223  2230801.089619419238.250387739
#Sta/Elev= 30
       0 2410.37    20.5 2400.89    33.8 2393.63    40.6 2389.46    55.9 2378.34
    64.4 2371.12    72.8 2362.88    76.8 2360.14    80.8 2359.34    88.9 2358.84
   100.8 2359.03   104.6 2359.48   124.9  2362.2   136.8 2362.11   152.6 2365.22
   160.9 2366.28   168.8 2366.49   196.6 2365.81   220.8 2366.37   236.8 2365.98
   244.8 2367.76   284.8 2372.91   288.8 2374.17   292.8 2376.01   316.9 2388.27
   321.2 2390.08   341.3 2396.31     368 2405.81   389.3 2415.86     399 2420.03
#Mann= 6 ,-1,0
       0     .12       0   74.37      .1       0    80.8    .045       0
   104.6      .1       0  174.37     .06       0  264.37      .1       0
#XS Ineff= 1 ,-1
  126.32398.9603 2371.66
Permanent Ineff=
       F
Bank Sta=80.8,104.6
XS Rating Curve= 0 ,0
Exp/Cntr(USF)=0,0
Exp/Cntr=0.3,0.1

Type RM Length L Ch R = 1 ,1055    ,294.8,303,312.1
XS GIS Cut Line= 3
2230491.82521866418756.0503839412230451.43150106418824.214782384
2230495.61212968419161.249863572
#Sta/Elev= 30
       0 2409.19    30.7 2394.42    47.8 2383.57    66.4 2370.25    71.1 2367.62
    80.2 2363.79    96.3 2360.26   124.6 2359.55   144.5 2361.49   160.9 2361.41
   181.1 2361.33   197.2 2359.46   213.3 2359.78   244.8  2357.1   253.7 2355.16
   269.6 2354.51     286 2353.79  290.782354.487   294.8 2356.82   298.3 2358.11
   314.2 2359.03   334.4 2358.82   342.4 2358.09   346.5 2359.45   358.6 2372.47
   369.7 2383.12   378.7 2390.89   390.8 2399.99   402.9 2407.81   419.2 2417.13
#Mann= 6 ,-1,0
       0     .12       0    71.1      .1       0   160.9     .12       0
   269.6    .045       0  290.78     .06       0   369.7      .1       0
Bank Sta=269.6,290.78
XS Rating Curve= 0 ,0
Exp/Cntr(USF)=0,0
Exp/Cntr=0.3,0.1

Type RM Length L Ch R = 1 ,752     ,266.9,277.3,287.5
XS GIS Cut Line= 3
2230372.46892069418733.2286222862230232.05449407418881.187356738
2230134.59327867419099.396983504
#Sta/Elev= 30
       0 2407.31      44 2381.49    88.2 2359.03    93.7 2357.96     119 2357.32
   169.9 2354.58   180.6 2353.17   192.9 2352.76   212.7 2354.24   230.3 2349.73
   234.6 2348.91     239 2349.71   243.4 2350.85   256.5 2351.25   265.3 2353.77
   279.6  2353.5   291.6 2354.59   313.5 2352.69     325 2350.64   339.8 2350.43
   343.2 2351.45   348.5 2354.49   350.8 2355.17   366.1 2356.01   370.5 2359.83
   380.2 2370.66   385.6 2375.87   396.7 2384.83     410 2393.83     443 2412.86
#Mann= 5 ,-1,0
       0     .12       0     160      .1       0   230.3    .045       0
     239      .1       0  353.98     .06       0
#XS Ineff= 2 , 0
             210 2363.29
Permanent Ineff=
       F       F
Bank Sta=230.3,239
XS Rating Curve= 0 ,0
Exp/Cntr(USF)=0,0
Exp/Cntr=0.3,0.1

Type RM Length L Ch R = 1 ,474     ,310.2,312.7,315.2
XS GIS Cut Line= 3
2230225.47914326418651.2791789272229860.67338123418860.821588955
2229820.27966363418951.707453545
#Sta/Elev= 30
       0 2398.54      43 2379.18    60.9  2369.6    84.5    2360    93.8 2357.46
   112.2 2356.08   126.1 2352.39   151.8 2348.94   166.4 2348.99   176.8 2348.05
   195.7 2349.27   219.2 2349.52   230.9 2349.07   245.5 2346.33   255.2 2345.68
     266 2344.47   273.7 2344.68   278.3 2345.82   282.9 2348.94   287.5  2349.6
   301.9 2348.84   341.1 2348.91   356.7 2349.76   375.1 2351.88   421.4  2352.7
   429.8  2355.6   442.6 2362.63   456.1 2370.42   491.1 2392.15   520.2 2409.13
#Mann= 9 ,-1,0
       0      .1       0      70     .06       0     130      .1       0
     190     .06       0   255.2    .045       0   278.3     .06       0
     300     .05       0     330     .06       0     410      .1       0
#XS Ineff= 2 ,-1
       0  220.37 2356.08  286.77520.1613 2356.17
Permanent Ineff=
       F       F
Bank Sta=255.2,278.3
XS Rating Curve= 0 ,0
Exp/Cntr(USF)=0,0
Exp/Cntr=0.3,0.1

Type RM Length L Ch R = 1 ,162     ,52.3,52.3,52.3
XS GIS Cut Line= 4
2230175.28337777418546.4100012782229993.21591043418449.177378278
2229716.77076229418557.8687069872229599.37652053418879.756144078
#Sta/Elev= 30
       0 2395.23    12.6 2389.23    45.1 2371.58      67 2359.05      79 2350.36
      83  2348.2    87.5 2347.23     130 2345.82   237.6 2342.76   276.3 2343.84
   302.1  2343.3     315 2344.48   319.3 2343.89325.04212341.922   339.9 2340.92
349.64152341.854   401.6 2343.86   448.2 2342.14   466.4 2340.54   499.8 2341.32
     519 2343.94   558.1  2343.5   609.5 2345.07   643.8 2344.65   712.4  2347.2
   732.6  2348.5   758.2 2351.83     771 2352.23   796.2 2359.78   846.1 2379.61
#Mann= 8 ,-1,0
       0      .1       0      10     .06       0      70     .08       0
     130      .1       0325.0421    .045       0349.6415      .1       0
   396.4     .05       0  673.45      .1       0
#XS Ineff= 2 , 0
          318.31 2351.99  406.32         2351.62
Permanent Ineff=
       F       F
Bank Sta=325.0421,349.6415
XS Rating Curve= 0 ,0
Exp/Cntr(USF)=0,0
Exp/Cntr=0.3,0.1