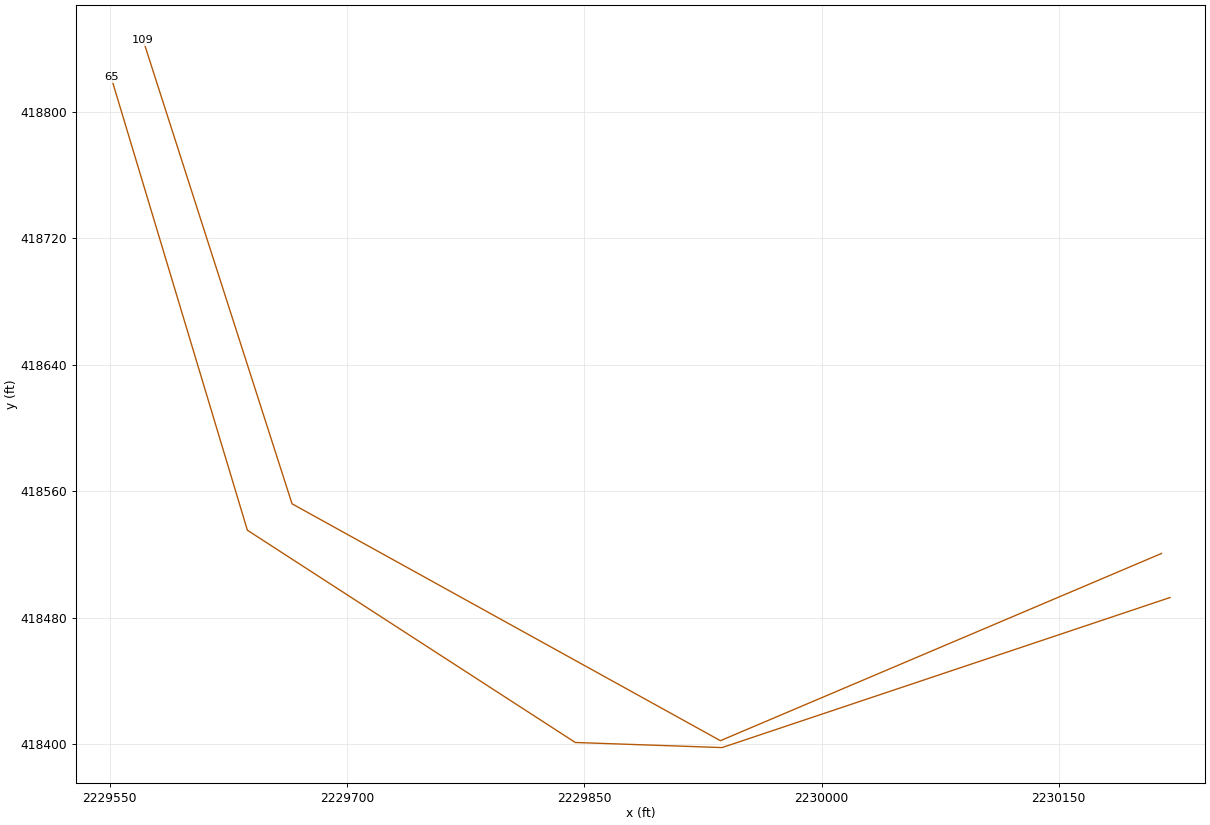
HEC-RAS study NFBEAVERCK.prj: NFBEAVERCK

--- NFBEAVERCK.g01 (geometry) --- (continued)

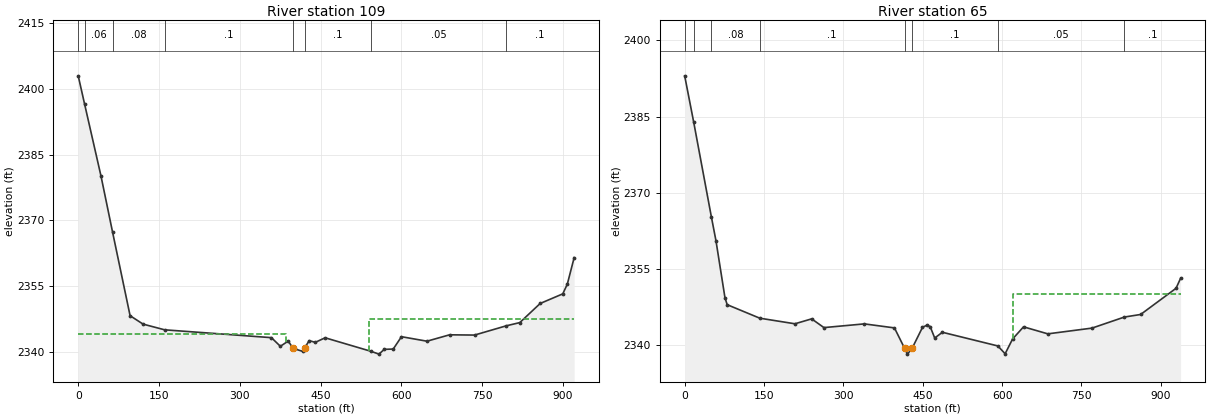
Type RM Length L Ch R = 1 ,109     ,44.1,44,44.1
XS GIS Cut Line= 4
2230215.01397346418520.6458155352229936.08755726418402.259040812
 2229665.2329666418552.0362482272229571.06166853418845.312576519
#Sta/Elev= 30
       0 2402.99    11.8 2396.56    42.2 2380.16    63.9 2367.23    96.3 2348.23
   120.4 2346.31   160.4 2345.01   358.6 2343.22   375.2 2341.25   389.8 2342.44
   398.9 2340.77   416.9 2340.08  420.212340.857   428.7 2342.54     440 2342.15
   458.3 2343.19   543.5  2340.1   558.2 2339.46     568 2340.55   584.7 2340.62
     600 2343.44   647.3 2342.41   689.3 2343.87   735.6 2343.81   794.4 2345.92
   819.6 2346.66   857.4 2351.02   899.4 2353.22   907.8 2355.43   920.5 2361.49
#Mann= 8 ,-1,0
       0      .1       0    11.8     .06       0    63.9     .08       0
   160.4      .1       0   398.9    .045       0  420.21      .1       0
   543.5     .05       0   794.4      .1       0
#XS Ineff= 2 , 0
             385    2344  538.95         2347.55
Permanent Ineff=
       F       F
Bank Sta=398.9,420.21
XS Rating Curve= 0 ,0
Exp/Cntr(USF)=0,0
Exp/Cntr=0.3,0.1

Type RM Length L Ch R = 1 ,65      ,,,
XS GIS Cut Line= 5
2230220.35203181418492.7730090632229937.13808967418397.903519756
2229844.32414241418401.1287148352229636.99586125418535.334877669
 2229550.8928361418821.581577933
#Sta/Elev= 30
       0 2393.01    17.1 2383.87    50.4 2365.29    59.2 2360.53    76.1 2349.38
    80.3 2347.98     142 2345.32   208.4 2344.22     240 2345.19   263.2 2343.47
   339.7  2344.2   396.5 2343.41   415.6 2339.41   421.1 2338.25     430 2339.42
   449.5 2343.52   457.9 2343.95     464 2343.67   472.6 2341.42   487.1 2342.55
   591.9 2339.86   605.7 2338.32   619.8 2341.23   640.5 2343.62   686.4 2342.24
   769.9 2343.37   831.2 2345.55   861.8 2346.05   928.7  2351.2   937.4 2353.18
#Mann= 8 ,-1,0
       0      .1       0    17.1     .06       0    50.4     .08       0
     142      .1       0   415.6    .045       0     430      .1       0
   591.9     .05       0   831.2      .1       0
#XS Ineff= 2 , 0
                             620            2350
Permanent Ineff=
       F       F
Bank Sta=415.6,430
XS Rating Curve= 0 ,0
Exp/Cntr(USF)=0,0
Exp/Cntr=0.3,0.1
LCMann Table=0

Chan Stop Cuts=-1
Use User Specified Reach Order=0
Composite Channel Slope=5